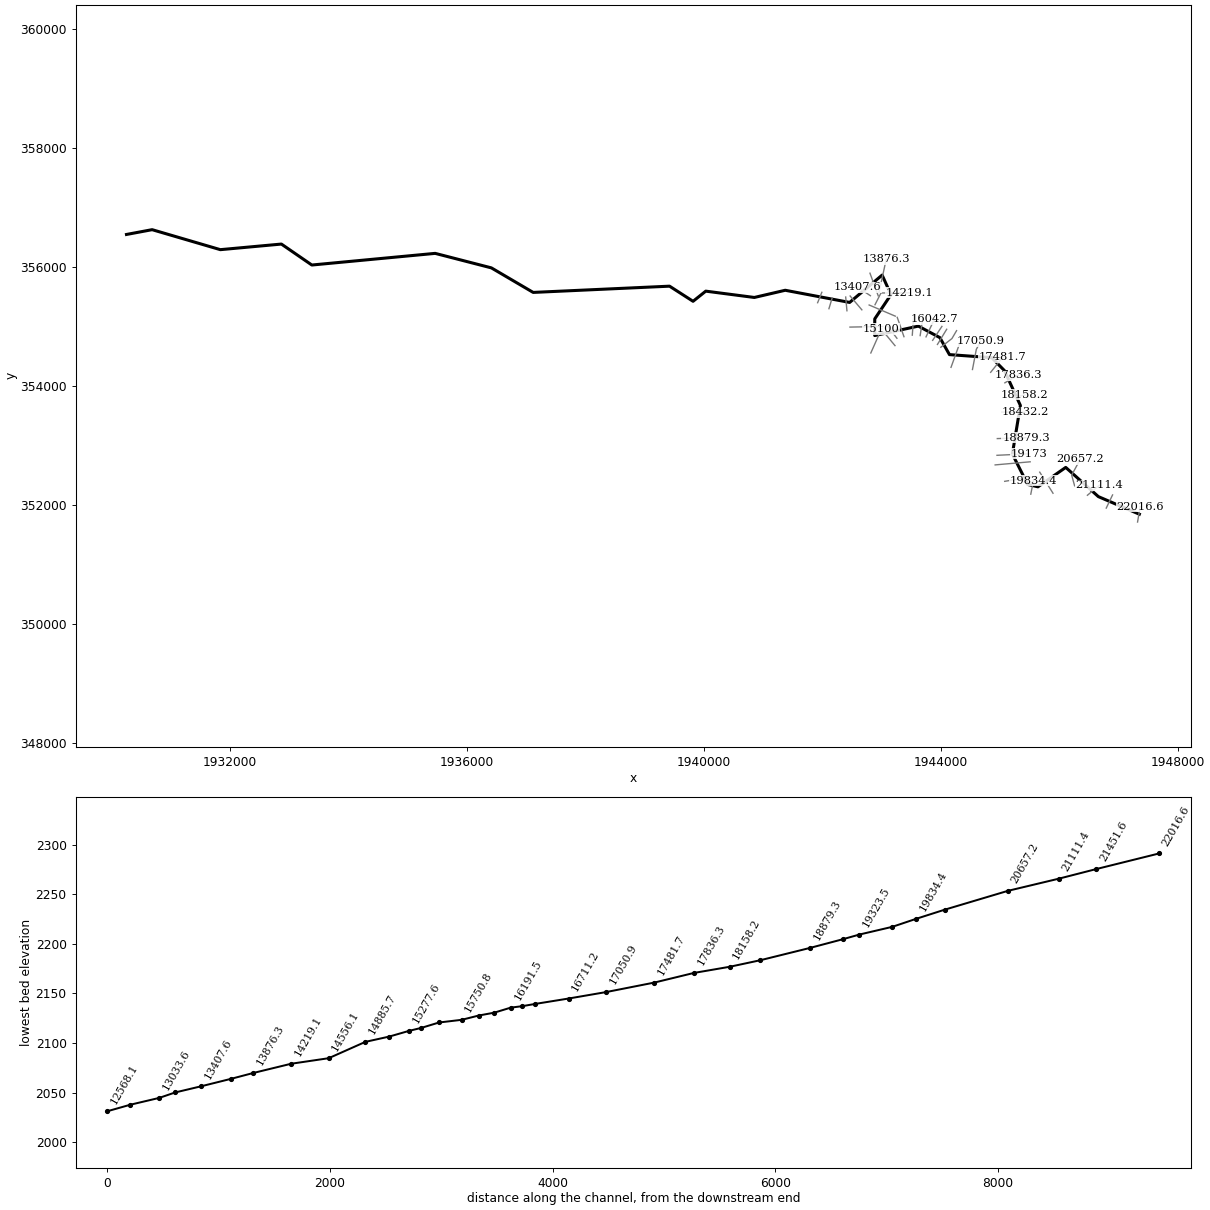
--- ELSEYRN.prj (project) ---

Proj Title=ELSEYRN
Current Plan=p01
Geom File=g01
Flow File=f01
Plan File=p01
DSS Export Rating Curves=0
DSS Export Rating Curve Sorted=0
DSS Export Volume Flow Curves=0
DXF OffsetX=0
DXF OffsetY=0
DXF ScaleX=0
DXF ScaleY=0

--- ELSEYRN.p01 (plan) ---

Plan Title=Floodplain
Program Version=4.00
Geom File=g01
Flow File=f01
K Sum by GR=0
Std Step Tol=0.01
Critical Tol=0.01
Num of Std Step Trials=20
Max Error Tol=0.3
Flow Tol Ratio=0.001
Split Flow NTrial=30
Split Flow Tol=0.02
Split Flow Ratio=0.02
Log Output Level=0
Friction Slope Method=1
Unsteady Friction Slope Method=2
Unsteady Bridges Friction Slope Method=1
Global Log Level=0
CheckData=False
Run HTab=0
Run UNet=0
Run PostProcess=0
UNET Theta=0
UNET Theta Warmup=0
UNET ZTol=0
UNET ZSATol=0
UNET MxIter=0
UNET MaxInSteps=0
UNET DtIC=0
UNET DtMin=0
UNET MaxCRTS=0
UNET WFStab=0
UNET SFStab=0
UNET WFX=0
UNET SFX=0
UNET DSS MLevel=0
UNET DZMax Abort=0
UNET Convert EG Bridges=0
UNET Use Existing IB Tables=0
UNET Froude Limit=0
UNET Froude Power=0
Write IC File=0
Echo Input=False
Echo Output=False
Write Detailed=0

--- ELSEYRN.f01 (steady flow) ---

Flow Title=NFF Regression Equation
Program Version=4.10
Number of Profiles= 1
Profile Names=P100yr
River Rch & RM=ELSEYRN,Main            ,22016.6
587.5026
River Rch & RM=ELSEYRN,Main            ,21111.4
593.9267
River Rch & RM=ELSEYRN,Main            ,19323.5
659.3418
River Rch & RM=ELSEYRN,Main            ,18432.2
850.9707
River Rch & RM=ELSEYRN,Main            ,18432.2
688.2391
River Rch & RM=ELSEYRN,Main            ,14219.1
895.9497
River Rch & RM=ELSEYRN,Main            ,13876.3
1000.236
River Rch & RM=ELSEYRN,Main            ,9012.1
 1080.57
River Rch & RM=ELSEYRN,Main            ,4434.6
1190.966
River Rch & RM=ELSEYRN,Main            ,246.6
1291.531
Boundary for River Rch & Prof#=ELSEYRN,Main            , 1
Up Type= 0
Dn Type= 3
Dn Slope=0.0316
DSS Import GetInterval= 0
DSS Import GetPeak= 0
DSS Import FillOption= 0

--- ELSEYRN.g01 (geometry) ---

Geom Title=USGS 10m DEM
Program Version=4.10

River Reach=ELSEYRN         ,Main
Reach XY= 30
       1947344.1      351841.095     1946652.328      352137.209
     1946101.705      352628.351     1945632.315      352301.807
     1945458.509      352342.376      1945200.91      352853.566
     1945336.498      353669.962     1945067.364      354256.184
     1944853.167      354473.745     1944139.315      354525.224
     1943977.263      354810.992     1943614.187      355004.708
     1942877.753      354845.842     1942878.232      355125.819
     1943151.669      355533.371     1943003.212      355862.759
     1942454.328      355402.742     1941367.359      355607.473
     1940845.663      355486.381     1940025.996      355592.673
      1939811.67      355421.909     1939414.731      355676.312
     1937113.069      355571.262     1936407.544      355984.036
     1935458.934      356227.984      1933377.44      356032.027
     1932863.671       356384.46     1931833.163      356290.365
      1930681.69      356626.505     1930248.887      356545.904

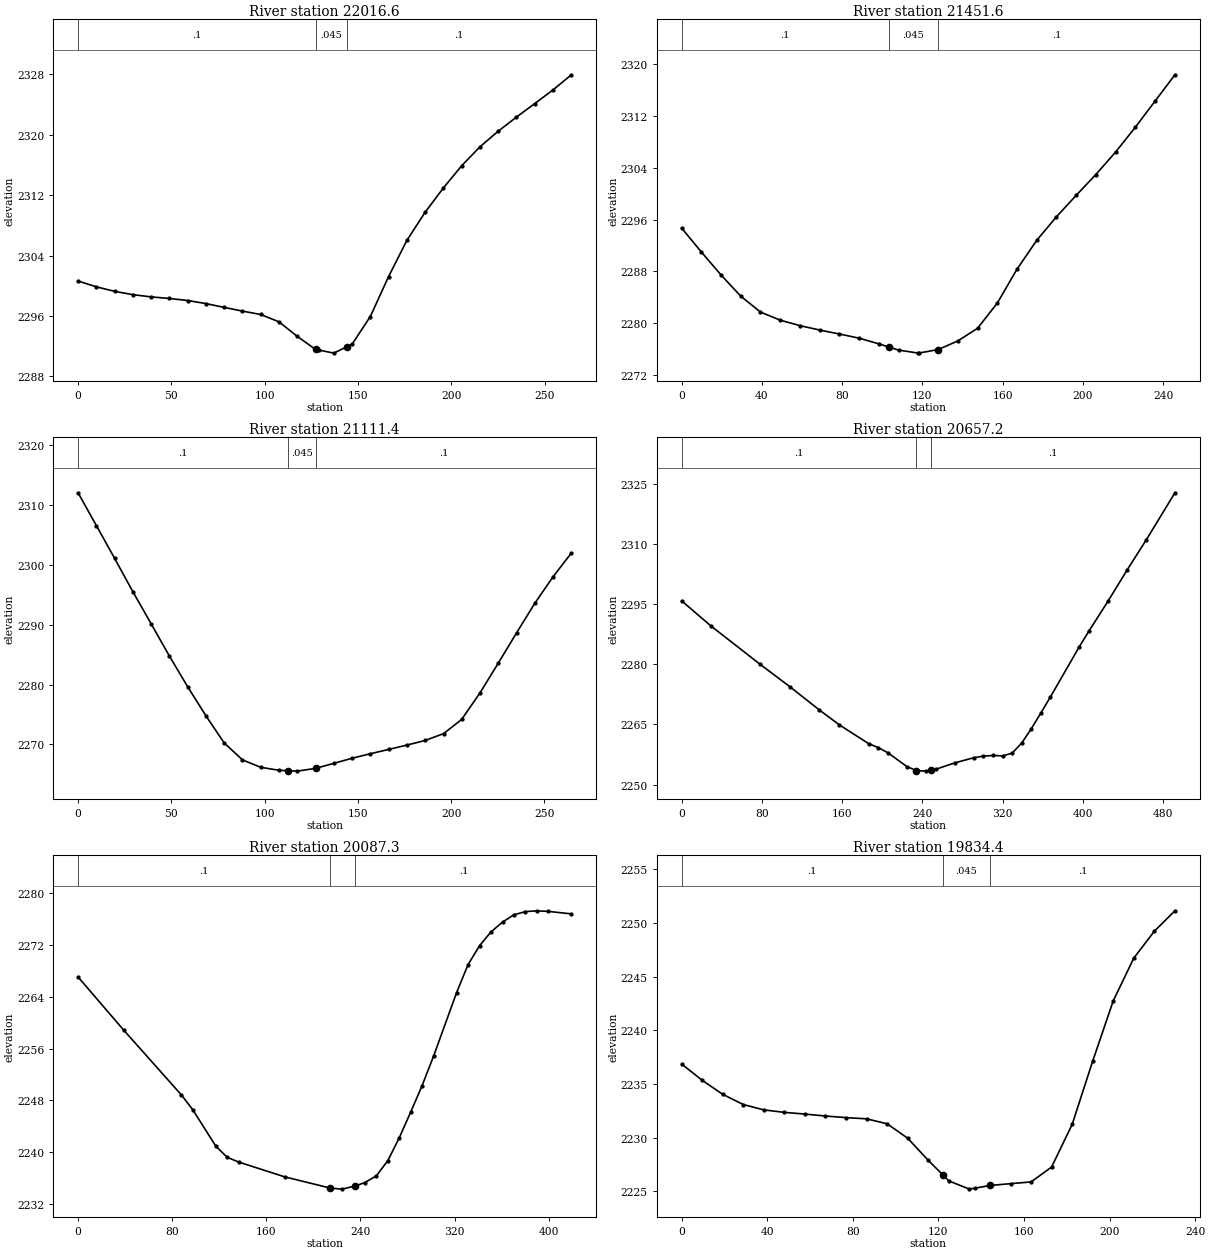
Type RM Length L Ch R = 1 ,22016.6 ,572.1,565,560.2
XS GIS Cut Line= 2
      1947313.94      351709.501     1947358.211      351969.918
#Sta/Elev= 30
       0 2300.63     9.8 2299.86    19.6 2299.26    29.4 2298.82    39.1 2298.53
    48.9 2298.32    58.7 2298.05    68.5 2297.64    78.3 2297.14      88 2296.65
    97.8  2296.2   107.6 2295.23   117.4  2293.3   127.2 2291.58   128.9  2291.5
     137 2291.09   143.9 2291.93   146.8 2292.28   156.5 2295.92   166.3 2301.21
   176.1    2306   185.9 2309.73   195.7 2312.95   205.4 2315.86   215.2 2318.37
     225 2320.44   234.8 2322.31   244.6  2324.1   254.4 2325.91   264.2  2327.9
#Mann= 3 , 0 , 0
       0      .1       0   127.2    .045       0   143.9      .1       0
Bank Sta=127.2,143.9
XS Rating Curve= 0 ,0
Exp/Cntr=0.3,0.1

Type RM Length L Ch R = 1 ,21451.6 ,349.8,340.2,330.6
XS GIS Cut Line= 2
     1946785.294      351943.876     1946892.065       352165.23
#Sta/Elev= 28
       0 2294.69     9.8    2291    19.7 2287.41    29.5 2284.14    39.3 2281.69
    49.2 2280.43      59 2279.59    68.8 2278.91    78.6  2278.3    88.5 2277.65
    98.3 2276.77   103.2 2276.29   108.1 2275.81     118 2275.34   118.2 2275.35
   127.8 2275.89   137.6 2277.22   147.5 2279.19   157.3 2283.08   167.1 2288.31
     177 2292.81   186.8 2296.44   196.6 2299.74   206.4 2302.97   216.3 2306.46
   226.1 2310.29   235.9 2314.32   245.8 2318.39
#Mann= 3 , 0 , 0
       0      .1       0   103.2    .045       0   127.8      .1       0
Bank Sta=103.2,127.8
XS Rating Curve= 0 ,0
Exp/Cntr=0.3,0.1

Type RM Length L Ch R = 1 ,21111.4 ,445.2,454.2,462.3
XS GIS Cut Line= 2
     1946467.586      352160.022     1946670.711      352329.293
#Sta/Elev= 30
       0 2312.07     9.8  2306.6    19.6  2301.1    29.4 2295.52    39.2 2290.15
      49 2284.75    58.8 2279.61    68.6 2274.76    78.3 2270.26    88.1 2267.42
    97.9 2266.18   107.7 2265.68   112.4 2265.61   117.5 2265.54   127.3    2266
   127.4 2266.01   137.1 2266.84   146.9  2267.7   156.7 2268.45   166.5 2269.17
   176.3  2269.9   186.1 2270.67   195.9 2271.81   205.6 2274.18   215.4 2278.61
   225.2 2283.58     235 2288.64   244.8  2293.6   254.6 2298.04   264.4    2302
#Mann= 3 , 0 , 0
       0      .1       0   112.4    .045       0   127.4      .1       0
Bank Sta=112.4,127.4
XS Rating Curve= 0 ,0
Exp/Cntr=0.3,0.1

Type RM Length L Ch R = 1 ,20657.2 ,545.3,569.9,594.7
XS GIS Cut Line= 3
      1946251.44      352318.876     1946201.961      352498.564
     1946347.794      352766.793
#Sta/Elev= 30
       0 2295.78    29.4 2289.48    78.5 2279.92   107.9 2274.39   137.3 2268.59
     157 2264.92   186.4 2260.21   195.9 2259.24   205.5 2257.95   224.5 2254.51
   233.9 2253.51   243.6 2253.36   248.9 2253.61   253.2 2253.81   272.2 2255.41
   291.3  2256.7   300.9  2257.1   310.4 2257.26     320 2257.15   329.5 2257.85
     339 2260.35   348.6 2263.94   358.1 2267.84   367.6 2271.83   396.3  2284.3
   405.8 2288.17   424.9 2295.63     444 2303.44   463.1 2310.93   491.7 2322.68
#Mann= 3 , 0 , 0
       0      .1       0   233.9    .045       0   248.9      .1       0
Bank Sta=233.9,248.9
XS Rating Curve= 0 ,0
Exp/Cntr=0.3,0.1

Type RM Length L Ch R = 1 ,20087.3 ,270.3,252.9,235.2
XS GIS Cut Line= 2
     1945886.944      352193.801     1945662.898      352548.043
#Sta/Elev= 28
       0 2267.05      39  2258.8    87.7 2248.86    97.5 2246.54     117 2240.94
   126.7 2239.21   136.5 2238.47   175.5 2236.19   214.4 2234.45   224.2 2234.29
   235.7 2234.78   243.7 2235.31   253.4 2236.33   263.2 2238.68   272.9  2242.2
   282.7 2246.21   292.4 2250.29   302.2 2254.87   321.7 2264.65   331.4 2268.96
   341.2 2271.89   350.9 2274.01   360.7 2275.53   370.4 2276.66   380.2 2277.15
   389.9 2277.27   399.6 2277.18   419.2  2276.8
#Mann= 3 , 0 , 0
       0      .1       0   214.4    .045       0   235.7      .1       0
Bank Sta=214.4,235.7
XS Rating Curve= 0 ,0
Exp/Cntr=0.3,0.1

Type RM Length L Ch R = 1 ,19834.4 ,244.9,216.2,187.5
XS GIS Cut Line= 2
     1945511.857      352178.251     1945557.083      352404.305
#Sta/Elev= 27
       0 2236.86     9.6 2235.35    19.2 2234.04    28.8 2233.09    38.4 2232.59
      48 2232.36    57.6  2232.2    67.2 2232.02    76.8 2231.87    86.4 2231.76
    96.1 2231.29   105.7 2229.94   115.3 2227.88   122.1 2226.53   124.9 2225.97
   134.5 2225.21   137.1  2225.3   144.1 2225.55   153.7 2225.72   163.3 2225.88
   172.9 2227.27   182.5 2231.24   192.1 2237.14   201.7 2242.75   211.3 2246.73
   220.9 2249.23   230.5 2251.13
#Mann= 3 , 0 , 0
       0      .1       0   122.1    .045       0   144.1      .1       0
Bank Sta=122.1,144.1
XS Rating Curve= 0 ,0
Exp/Cntr=0.3,0.1

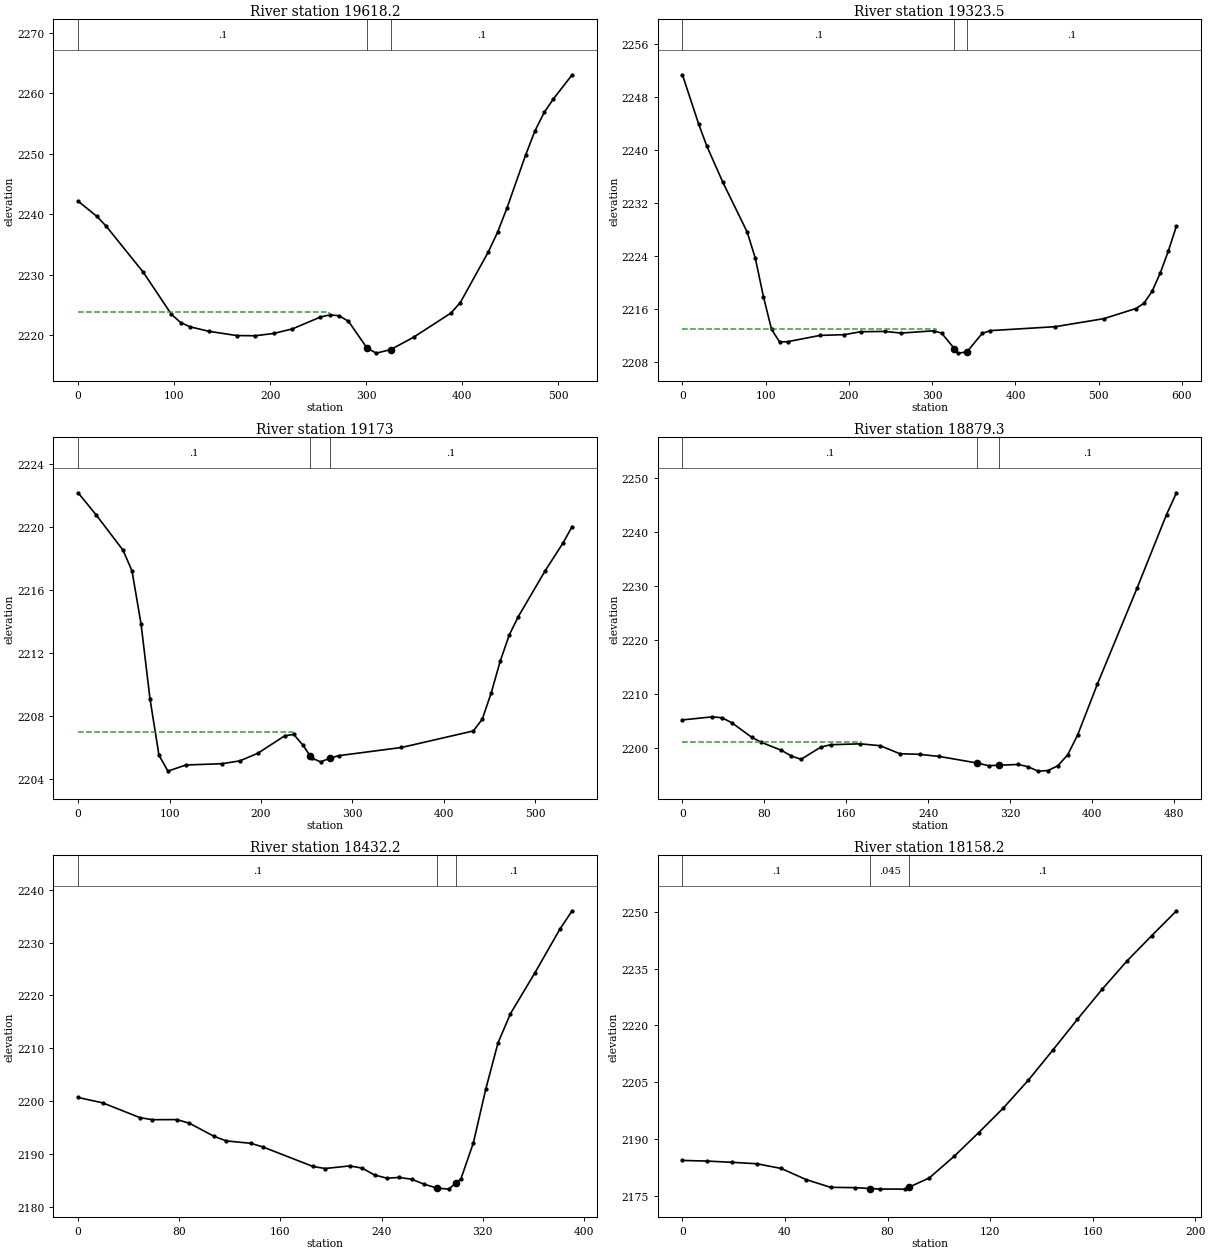
Type RM Length L Ch R = 1 ,19618.2 ,295.2,294.7,294.3
XS GIS Cut Line= 2
     1945071.753      352394.397     1945579.565      352475.126
#Sta/Elev= 30
       0 2242.19    19.4 2239.68    29.1 2238.07    67.9 2230.41      97 2223.49
   106.7 2222.11   116.4 2221.41   135.8 2220.67   164.9 2219.96   184.3 2219.92
   203.7 2220.31   223.1 2221.06   252.2 2223.02     262 2223.38   271.6 2223.23
   281.4 2222.32   300.8 2217.87   310.4 2217.05   325.4 2217.64   349.3 2219.69
   388.1 2223.68   397.8 2225.41   426.9 2233.76   436.6 2237.04   446.3 2241.01
   465.7 2249.76   475.4 2253.77   485.1 2256.85   494.8 2259.11   514.2 2263.08
#Mann= 3 , 0 , 0
       0      .1       0   300.8    .045       0   325.4      .1       0
#XS Ineff= 2 , 0
          261.13 2223.82
Permanent Ineff=
       F       F
Bank Sta=300.8,325.4
XS Rating Curve= 0 ,0
Exp/Cntr=0.3,0.1

Type RM Length L Ch R = 1 ,19323.5 ,151,150.5,149.4
XS GIS Cut Line= 2
     1944910.294      352670.439      1945501.44      352722.522
#Sta/Elev= 30
       0 2251.34    19.5 2243.89    29.2  2240.6    48.6 2235.09    77.8 2227.58
    87.6  2223.6    97.3 2217.82     107  2212.9   116.7 2210.99   126.5 2211.03
   165.4 2211.98   194.6 2212.09     214 2212.53   243.2 2212.58   262.7 2212.33
   301.6 2212.67   311.3 2212.33   326.6 2209.99   330.8  2209.3   341.6 2209.47
     360 2212.27   369.7  2212.7   447.5 2213.29   505.9  2214.5   544.8 2216.04
   554.5 2216.85   564.2 2218.65     574 2221.42   583.7 2224.73   593.4  2228.5
#Mann= 3 , 0 , 0
       0      .1       0   326.6    .045       0   341.6      .1       0
#XS Ineff= 2 , 0
          304.23 2212.99
Permanent Ineff=
       F       F
Bank Sta=326.6,341.6
XS Rating Curve= 0 ,0
Exp/Cntr=0.3,0.1

Type RM Length L Ch R = 1 ,19173   ,294.1,293.7,293.7
XS GIS Cut Line= 2
     1944941.544      352831.897     1945481.128      352857.864
#Sta/Elev= 30
       0 2222.19    19.6  2220.8    49.1 2218.55    58.9 2217.24    68.8 2213.88
    78.6 2209.12    88.4 2205.54    98.2 2204.53   117.9 2204.92   157.2    2205
   176.8 2205.18   196.4 2205.66   225.9 2206.77   235.7 2206.86   245.6  2206.2
   254.1 2205.47   255.4 2205.36   265.2 2205.12     275 2205.34   284.8 2205.51
   353.6 2206.03   432.2 2207.08     442 2207.83   451.8 2209.51   461.6 2211.51
   471.4 2213.16   481.3 2214.33   510.7 2217.24   530.4 2219.02   540.2 2220.05
#Mann= 3 , 0 , 0
       0      .1       0   254.1    .045       0     275      .1       0
#XS Ineff= 2 , 0
          234.93 2207.03
Permanent Ineff=
       F       F
Bank Sta=254.1,275
XS Rating Curve= 0 ,0
Exp/Cntr=0.3,0.1

Type RM Length L Ch R = 1 ,18879.3 ,447.5,447,446.5
XS GIS Cut Line= 2
     1944946.753      353113.147     1945429.045      353126.961
#Sta/Elev= 30
       0 2205.26      29 2205.82    38.6 2205.66    48.2 2204.74    67.6 2202.06
    77.2  2201.1    96.5 2199.66   106.2 2198.61   115.8 2197.98   135.1 2200.23
   144.8 2200.68   173.7 2200.84     193  2200.5   212.3 2199.02   231.6  2198.9
   250.9 2198.51   287.8  2197.3   299.1  2196.8   308.8 2196.89   328.1 2197.03
   337.7  2196.6   347.4  2195.8     357  2195.9   366.7  2196.8   376.3 2198.82
     386 2202.48   405.3 2211.88   443.9 2229.54   472.8 2243.18   482.5  2247.2
#Mann= 3 , 0 , 0
       0      .1       0   287.8    .045       0   308.8      .1       0
#XS Ineff= 2 , 0
          173.94 2201.17
Permanent Ineff=
       F       F
Bank Sta=287.8,308.8
XS Rating Curve= 0 ,0
Exp/Cntr=0.3,0.1

Type RM Length L Ch R = 1 ,18432.2 ,268.5,274.1,279.4
XS GIS Cut Line= 2
     1945022.273      353558.459     1945412.898      353555.855
#Sta/Elev= 30
       0  2200.7    19.5 2199.68    48.8  2196.9    58.6  2196.5    78.1 2196.52
    87.9 2195.84   107.4 2193.36   117.2 2192.49   136.7 2192.03   146.5 2191.31
   185.6 2187.66   195.3 2187.27   214.8 2187.76   224.6 2187.34   234.4 2186.04
   244.2 2185.44   253.9 2185.58   263.7 2185.24   273.4 2184.32   283.7 2183.57
     293 2183.37   298.7 2184.52   302.7 2185.32   312.5  2192.1   322.3 2202.26
     332 2211.02   341.8 2216.53   361.3 2224.32   380.9 2232.53   390.6    2236
#Mann= 3 , 0 , 0
       0      .1       0   283.7    .045       0   298.7      .1       0
Bank Sta=283.7,298.7
XS Rating Curve= 0 ,0
Exp/Cntr=0.3,0.1

Type RM Length L Ch R = 1 ,18158.2 ,318.9,321.8,327
XS GIS Cut Line= 2
      1945220.19      353803.251      1945407.69      353847.522
#Sta/Elev= 23
       0 2184.36     9.6 2184.19    19.3 2183.87    28.9 2183.49    38.5 2182.25
    48.2 2179.32    57.8 2177.26    67.4 2177.18    73.3 2176.95    77.1 2176.81
    86.7 2176.79    88.3 2177.28    96.3 2179.75     106 2185.46   115.6 2191.73
   125.2 2198.21   134.9 2205.51   144.5 2213.49   154.1 2221.62   163.8 2229.59
   173.4 2236.98     183 2243.63   192.7 2250.22
#Mann= 3 , 0 , 0
       0      .1       0    73.3    .045       0    88.3      .1       0
Bank Sta=73.3,88.3
XS Rating Curve= 0 ,0
Exp/Cntr=0.3,0.1

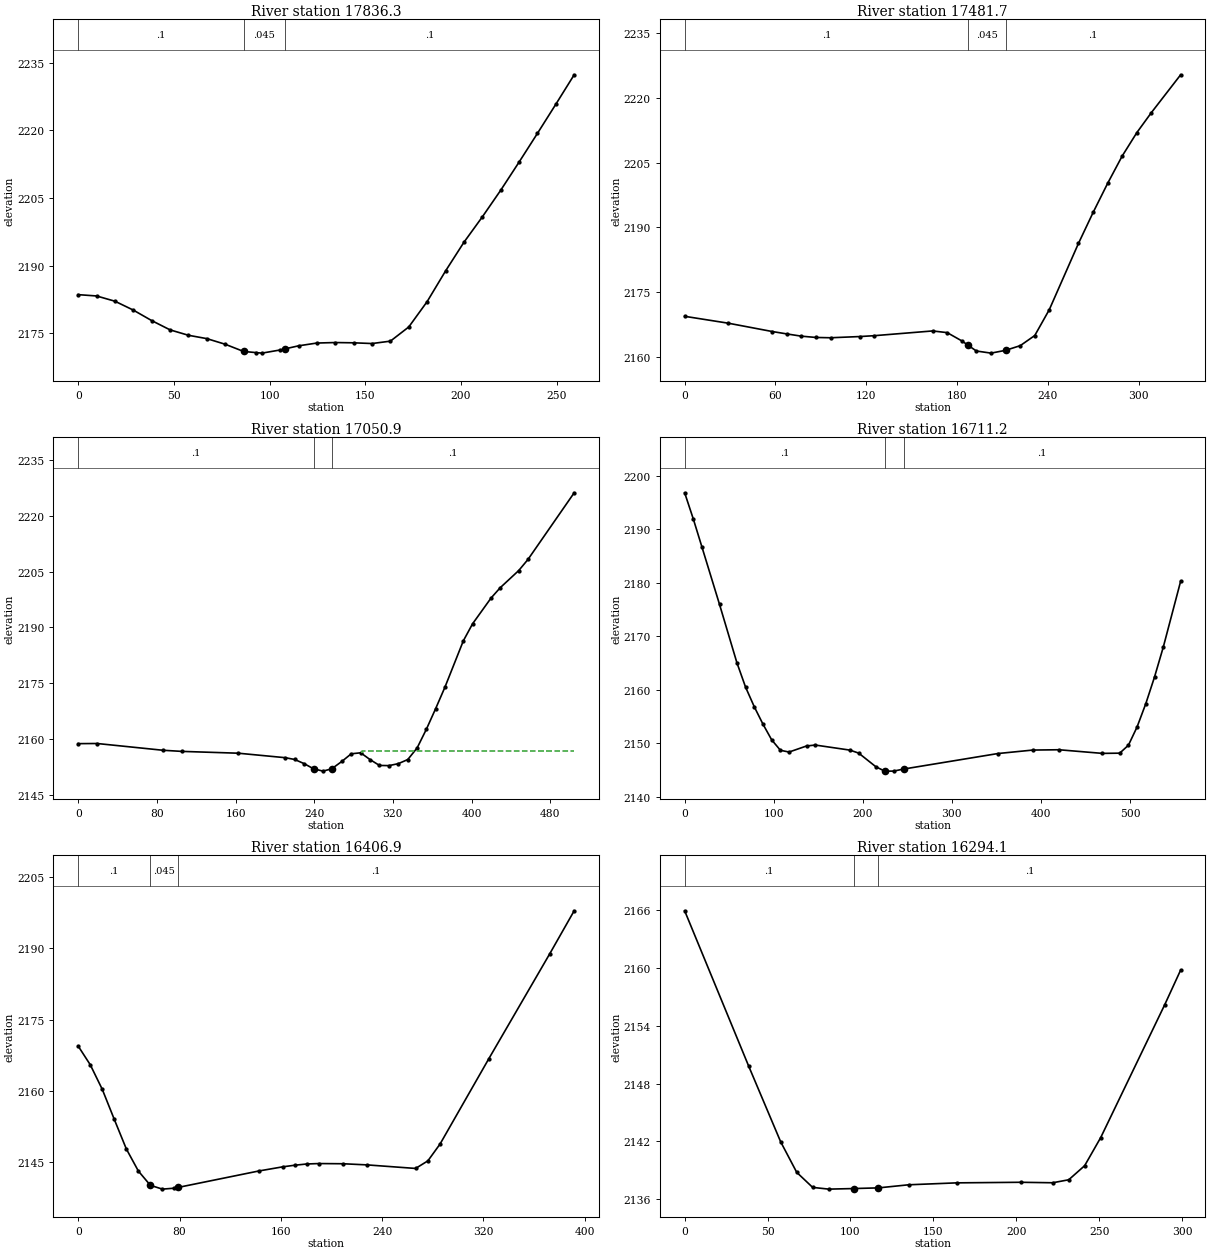
Type RM Length L Ch R = 1 ,17836.3 ,345.9,354.7,363.4
XS GIS Cut Line= 2
     1945074.357      354050.647     1945298.315      354180.855
#Sta/Elev= 30
       0 2183.55     9.6 2183.26    19.2 2182.09    28.8 2180.12    38.4 2177.79
      48 2175.73    57.6 2174.53    67.2 2173.79    76.8 2172.54    86.4 2170.94
    93.1 2170.68      96 2170.57   105.5 2171.27   108.1 2171.52   115.1 2172.19
   124.7 2172.81   134.3 2172.92   143.9 2172.86   153.5  2172.7   163.1 2173.23
   172.7 2176.38   182.3 2182.01   191.9  2188.8   201.5 2195.17   211.1  2200.8
   220.7 2206.71   230.3 2212.96   239.9 2219.34   249.5  2225.8   259.1 2232.35
#Mann= 3 , 0 , 0
       0      .1       0    86.4    .045       0   108.1      .1       0
Bank Sta=86.4,108.1
XS Rating Curve= 0 ,0
Exp/Cntr=0.3,0.1

Type RM Length L Ch R = 1 ,17481.7 ,419.9,430.7,441
XS GIS Cut Line= 2
     1944834.773       354227.73     1945040.503      354482.939
#Sta/Elev= 26
       0 2169.41    28.9 2167.81    57.8 2165.89    67.5 2165.33    77.1 2164.81
    86.8 2164.51    96.4 2164.44   115.7 2164.72   125.3 2164.92   163.9 2166.02
   173.5 2165.63   183.2 2163.71   187.5 2162.66   192.8 2161.37   202.5 2160.88
   212.1 2161.53   221.8 2162.61   231.4 2164.96     241 2170.95   260.3 2186.32
     270  2193.5   279.6 2200.24   289.2 2206.56   298.9 2211.99   308.5 2216.62
   327.8 2225.36
#Mann= 3 , 0 , 0
       0      .1       0   187.5    .045       0   212.1      .1       0
Bank Sta=187.5,212.1
XS Rating Curve= 0 ,0
Exp/Cntr=0.3,0.1

Type RM Length L Ch R = 1 ,17050.9 ,343.3,339.7,336.1
XS GIS Cut Line= 3
     1944527.482      354274.605     1944592.586      354613.147
     1944668.107      354753.772
#Sta/Elev= 30
       0 2158.73    19.2 2158.77    86.2 2156.95   105.3 2156.65   162.8 2156.16
   210.7 2154.95   220.2 2154.47   229.8 2153.35   239.4 2151.96     249 2151.34
   257.8 2151.96   268.1 2153.94   277.7    2156   287.3 2156.27   296.9 2154.43
   306.4 2152.87     316 2152.82   325.6 2153.35   335.2 2154.46   344.7 2157.58
   354.1  2162.6   363.5 2168.13   372.9 2173.87   391.7 2186.39   401.1 2190.97
   419.9  2197.9   429.2 2200.67     448 2205.28   457.4 2208.26   504.4 2226.19
#Mann= 3 , 0 , 0
       0      .1       0   239.4    .045       0   257.8      .1       0
#XS Ineff= 2 , 0
                          288.17         2156.62
Permanent Ineff=
       F       F
Bank Sta=239.4,257.8
XS Rating Curve= 0 ,0
Exp/Cntr=0.3,0.1

Type RM Length L Ch R = 1 ,16711.2 ,318.7,304.3,289.1
XS GIS Cut Line= 2
     1944165.503      354311.064     1944355.607      354834.501
#Sta/Elev= 30
       0 2196.84     9.8 2191.89    19.5 2186.64    39.1 2175.98    58.6 2165.08
    68.4 2160.48    78.2  2156.8    87.9 2153.57    97.7 2150.63   107.5 2148.68
   117.2 2148.35   136.8 2149.48   146.6 2149.66   185.6 2148.71   195.4 2148.15
   214.9 2145.57   224.7 2144.78   234.5 2144.78   245.9 2145.17   351.7 2148.07
   390.8 2148.72   420.1 2148.78     469  2148.1   488.5 2148.14   498.3 2149.63
     508 2153.04   517.8  2157.4   527.6 2162.39   537.4 2167.96   556.9 2180.28
#Mann= 3 , 0 , 0
       0      .1       0   224.7    .045       0   245.9      .1       0
Bank Sta=224.7,245.9
XS Rating Curve= 0 ,0
Exp/Cntr=0.3,0.1

Type RM Length L Ch R = 1 ,16406.9 ,104.3,112.8,121.3
XS GIS Cut Line= 3
     1943993.628      354649.605     1944181.128      354795.439
     1944259.253      354928.251
#Sta/Elev= 23
       0  2169.4     9.5 2165.48      19 2160.29    28.5 2153.95      38 2147.73
    47.5 2143.07      57 2140.06    66.5 2139.26      76 2139.46    78.9 2139.62
   142.5 2143.08   161.5 2143.96     171  2144.3   180.5 2144.56     190 2144.65
     209 2144.61     228 2144.37   266.4 2143.62   276.1 2145.22   285.7 2148.76
   324.2 2166.74   372.4  2188.9   391.6 2197.92
#Mann= 3 , 0 , 0
       0      .1       0      57    .045       0    78.9      .1       0
Bank Sta=57,78.9
XS Rating Curve= 0 ,0
Exp/Cntr=0.3,0.1

Type RM Length L Ch R = 1 ,16294.1 ,103.8,102.6,101.5
XS GIS Cut Line= 2
     1943936.336       354696.48     1944092.586      354951.689
#Sta/Elev= 17
       0 2165.92    38.6 2149.82    57.9 2141.97    67.6  2138.8    77.2 2137.24
    86.9 2137.06   101.9 2137.12   116.9 2137.19   135.1 2137.51   164.1 2137.71
   202.7 2137.77     222 2137.72   231.7 2138.03   241.3 2139.49     251 2142.41
   289.6 2156.18   299.2 2159.77
#Mann= 3 , 0 , 0
       0      .1       0   101.9    .045       0   116.9      .1       0
Bank Sta=101.9,116.9
XS Rating Curve= 0 ,0
Exp/Cntr=0.3,0.1

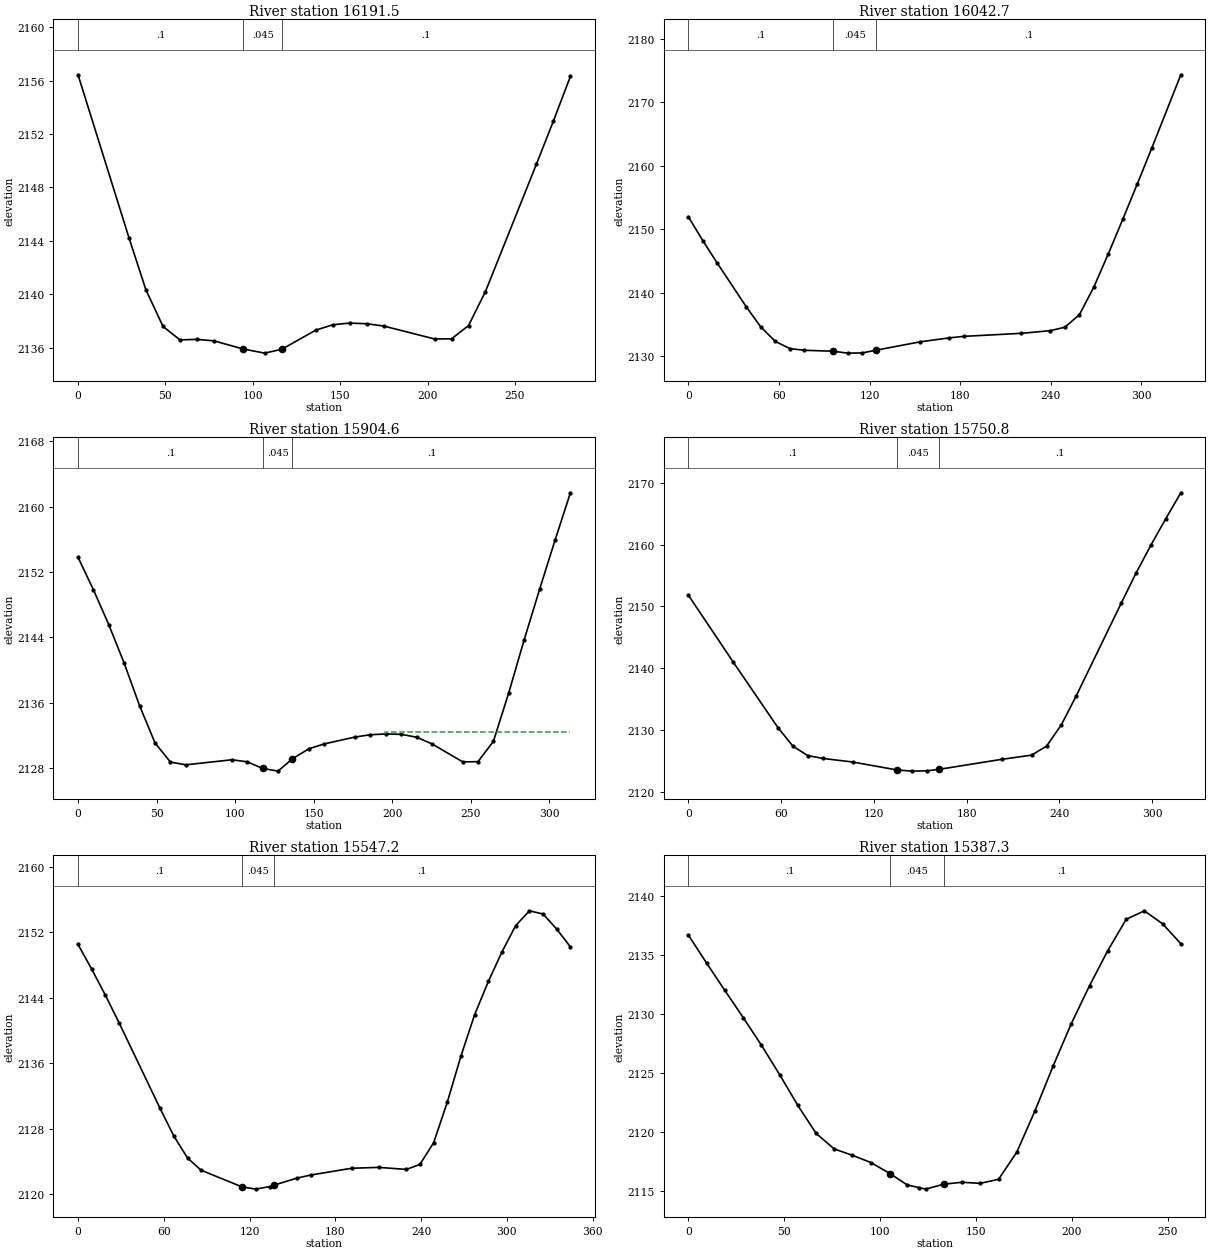
Type RM Length L Ch R = 1 ,16191.5 ,145.4,148.8,152.4
XS GIS Cut Line= 2
     1943855.694      354765.416     1944011.944      354999.791
#Sta/Elev= 22
       0 2156.43    29.1 2144.25    38.8 2140.35    48.6  2137.6    58.3 2136.59
      68 2136.63    77.7 2136.52    94.5 2135.91   106.8  2135.6   116.6 2135.89
     136 2137.32   145.7 2137.72   155.4 2137.85   165.1  2137.8   174.8 2137.63
     204 2136.66   213.7 2136.67   223.4 2137.66   233.1 2140.21   262.3 2149.76
     272 2152.98   281.7 2156.31
#Mann= 3 , 0 , 0
       0      .1       0    94.5    .045       0   116.6      .1       0
Bank Sta=94.5,116.6
XS Rating Curve= 0 ,0
Exp/Cntr=0.3,0.1

Type RM Length L Ch R = 1 ,16042.7 ,130.1,138.1,145.9
XS GIS Cut Line= 2
     1943743.628      354824.084     1943884.253      355118.355
#Sta/Elev= 25
       0 2151.98     9.6 2148.21    19.2 2144.66    38.4 2137.78      48 2134.62
    57.6 2132.35    67.2 2131.23    76.7 2130.96    95.9 2130.81   105.5 2130.51
   115.1 2130.54   124.3 2130.97   153.5 2132.29   172.7 2132.91   182.3 2133.15
   220.6 2133.63   239.8 2134.05   249.4 2134.59     259 2136.56   268.6 2140.92
   278.2 2146.17   287.8 2151.62   297.4 2157.18     307 2162.83   326.2 2174.36
#Mann= 3 , 0 , 0
       0      .1       0    95.9    .045       0   124.3      .1       0
Bank Sta=95.9,124.3
XS Rating Curve= 0 ,0
Exp/Cntr=0.3,0.1

Type RM Length L Ch R = 1 ,15904.6 ,153.7,153.8,154.4
XS GIS Cut Line= 2
     1943644.669      354844.918     1943691.544      355154.814
#Sta/Elev= 29
       0  2153.8     9.8 2149.83    19.6 2145.55    29.4 2140.84    39.2 2135.64
      49  2131.1    58.8 2128.76    68.6 2128.42    97.9 2129.04   107.7 2128.79
   117.5 2127.98   127.3 2127.65   136.5 2129.16   146.9 2130.38   156.7 2130.98
   176.3 2131.82   186.1  2132.1   195.9  2132.2   205.7 2132.15   215.5  2131.8
   225.3 2130.98   244.9 2128.78   254.6 2128.81   264.4  2131.3   274.2 2137.26
     284 2143.73   293.8  2149.9   303.6 2155.88   313.4 2161.69
#Mann= 3 , 0 , 0
       0      .1       0   117.5    .045       0   136.5      .1       0
#XS Ineff= 2 , 0
                          195.21         2132.39
Permanent Ineff=
       F       F
Bank Sta=117.5,136.5
XS Rating Curve= 0 ,0
Exp/Cntr=0.3,0.1

Type RM Length L Ch R = 1 ,15750.8 ,194.2,203.6,212.9
XS GIS Cut Line= 2
     1943511.857       354852.73     1943535.294      355170.439
#Sta/Elev= 21
       0 2151.81      29 2140.98    57.9 2130.37    67.6 2127.36    77.2 2125.83
    86.9 2125.37   106.2 2124.79   135.2 2123.49   144.8 2123.31   154.5 2123.36
   162.2  2123.6   202.7 2125.22     222  2125.9   231.7 2127.35   241.3 2130.81
     251 2135.54     280  2150.5   289.6 2155.38   299.3 2159.95   308.9 2164.23
   318.6 2168.41
#Mann= 3 , 0 , 0
       0      .1       0   135.2    .045       0   162.2      .1       0
Bank Sta=135.2,162.2
XS Rating Curve= 0 ,0
Exp/Cntr=0.3,0.1

Type RM Length L Ch R = 1 ,15547.2 ,152.6,159.9,167.2
XS GIS Cut Line= 2
     1943371.232      354826.689     1943257.921      355152.037
#Sta/Elev= 29
       0 2150.52     9.6 2147.49    19.1 2144.33    28.7 2140.95    57.4 2130.48
      67 2127.11    76.6 2124.42    86.1 2122.92   114.8 2120.88   124.4 2120.61
     134 2120.92   137.1  2121.1   153.1 2121.95   162.7 2122.33   191.4 2123.16
   210.5 2123.27   229.7 2123.02   239.2 2123.63   248.8 2126.28   258.4 2131.26
     268 2136.93   277.5 2141.94   287.1    2146   296.7 2149.64   306.2 2152.82
   315.8 2154.63   325.4 2154.24     335 2152.38   344.5 2150.22
#Mann= 3 , 0 , 0
       0      .1       0   114.8    .045       0   137.1      .1       0
Bank Sta=114.8,137.1
XS Rating Curve= 0 ,0
Exp/Cntr=0.3,0.1

Type RM Length L Ch R = 1 ,15387.3 ,108.7,109.7,110.7
XS GIS Cut Line= 2
     1943252.395      354800.138     1943096.453      355004.311
#Sta/Elev= 30
       0 2136.65     9.5 2134.28      19 2131.97    28.6 2129.67    38.1 2127.33
    47.6 2124.84    57.1 2122.23    66.6 2119.87    76.1 2118.55    85.6 2118.01
    95.2  2117.4   104.7 2116.51   105.3 2116.45   114.2  2115.5   120.3 2115.28
   123.7 2115.15   133.2 2115.57   142.7 2115.73   152.2 2115.64   161.8 2115.98
   171.3 2118.27   180.8 2121.77   190.3 2125.58   199.8 2129.17   209.3 2132.38
   218.8 2135.34   228.4 2137.99   237.9 2138.71   247.4 2137.61   256.9 2135.93
#Mann= 3 , 0 , 0
       0      .1       0   105.3    .045       0   133.2      .1       0
Bank Sta=105.3,133.2
XS Rating Curve= 0 ,0
Exp/Cntr=0.3,0.1

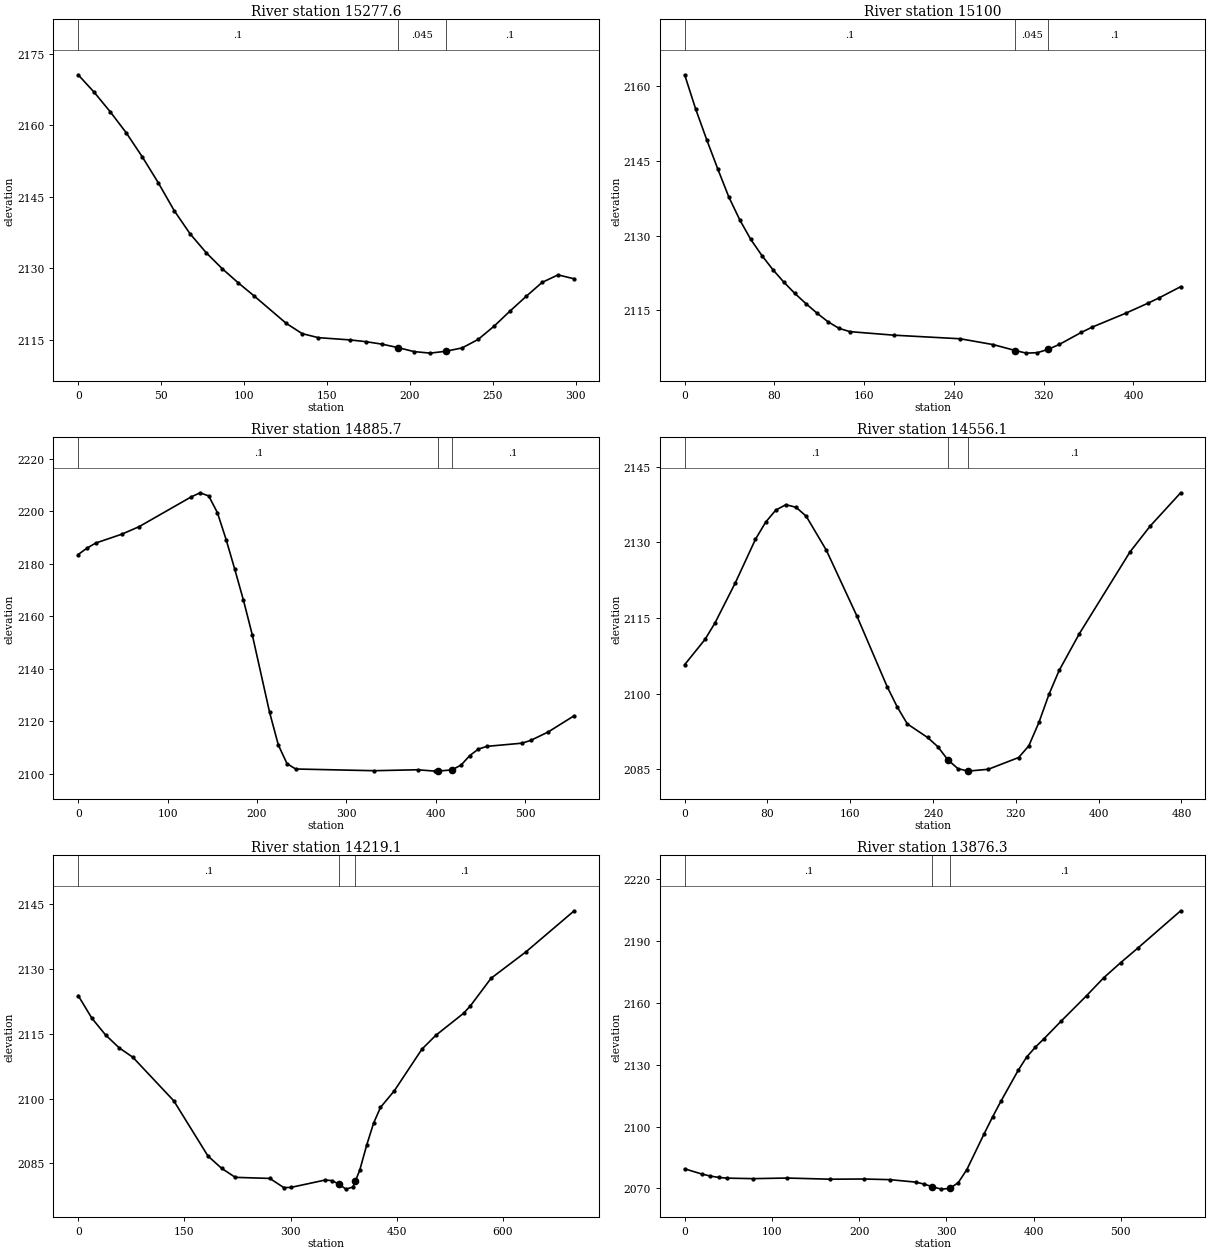
Type RM Length L Ch R = 1 ,15277.6 ,204,177.5,151.1
XS GIS Cut Line= 2
     1943219.843       354676.44     1943028.871      354906.475
#Sta/Elev= 30
       0 2170.57     9.6 2166.92    19.3 2162.82    28.9 2158.43    38.6 2153.37
    48.2 2147.96    57.9 2142.05    67.5 2137.18    77.2 2133.22    86.8 2129.89
    96.4 2126.94   106.1 2124.15   125.4 2118.41     135 2116.26   144.7 2115.41
     164 2114.93   173.6 2114.56   183.2 2114.04   192.9 2113.31   202.5 2112.48
   212.2 2112.16   221.8 2112.56   231.5 2113.26   241.1 2115.03   250.8 2117.84
   260.4 2121.01     270 2124.05   279.7 2127.01   289.3 2128.58     299 2127.76
#Mann= 3 , 0 , 0
       0      .1       0   192.9    .045       0   221.8      .1       0
Bank Sta=192.9,221.8
XS Rating Curve= 0 ,0
Exp/Cntr=0.3,0.1

Type RM Length L Ch R = 1 ,15100   ,240.3,214.3,188.2
XS GIS Cut Line= 2
     1942811.857      354552.742     1942991.979      354956.388
#Sta/Elev= 30
       0 2162.27     9.8  2155.4    19.6 2149.27    29.5 2143.38    39.3 2137.78
    49.1 2133.16    58.9 2129.24    68.8 2126.01    78.6 2123.18    88.4 2120.66
    98.2  2118.4     108 2116.37   117.9 2114.45   127.7 2112.72   137.5  2111.4
   147.3 2110.73   186.6 2110.02   245.6  2109.3     275 2108.13   294.7 2106.94
   304.5 2106.42   314.3 2106.51   324.1 2107.19     334 2108.18   353.6 2110.59
   363.4 2111.66   392.9 2114.41   412.5  2116.4   422.4 2117.46     442 2119.75
#Mann= 3 , 0 , 0
       0      .1       0   294.7    .045       0   324.1      .1       0
Bank Sta=294.7,324.1
XS Rating Curve= 0 ,0
Exp/Cntr=0.3,0.1

Type RM Length L Ch R = 1 ,14885.7 ,338.6,329.6,320
XS GIS Cut Line= 2
     1942459.773      354988.147     1943014.461      354998.564
#Sta/Elev= 30
       0 2183.58     9.7 2185.98    19.5 2187.93    48.7 2191.31    68.1 2194.18
   126.5 2205.54   136.3 2207.07     146 2205.89   155.7 2199.52   165.5 2189.24
   175.2 2177.87   184.9  2166.1   194.7 2153.03   214.1 2123.46   223.9 2111.01
   233.6 2103.91   243.3 2101.89   330.9 2101.24   379.6  2101.6   399.1 2101.08
     403  2101.1     418 2101.56   428.3 2103.38     438 2106.99   447.7 2109.49
   457.4 2110.52   496.4 2111.72   506.1 2112.77   525.6 2115.96   554.8 2122.17
#Mann= 3 , 0 , 0
       0      .1       0     403    .045       0     418      .1       0
Bank Sta=403,418
XS Rating Curve= 0 ,0
Exp/Cntr=0.3,0.1

Type RM Length L Ch R = 1 ,14556.1 ,328.2,337,346.1
XS GIS Cut Line= 2
     1942783.613      355359.673     1943224.586      355172.173
#Sta/Elev= 30
       0 2105.73    19.6 2110.72    29.3 2114.01    48.9 2121.94    68.4  2130.6
    78.2 2133.98      88 2136.38    97.8 2137.46   107.6 2136.94   117.4 2135.18
   136.9 2128.42   166.2 2115.47   195.6 2101.38   205.4 2097.33   215.1 2093.98
   234.7 2091.28   244.5 2089.48   254.3 2086.85     264 2085.11   273.8 2084.61
   293.4 2084.98   322.7 2087.31   332.5 2089.62   342.3 2094.28     352 2099.84
   361.8 2104.57   381.4 2111.89   430.3 2128.09   449.8 2133.22   479.2 2139.81
#Mann= 3 , 0 , 0
       0      .1       0   254.3    .045       0   273.8      .1       0
Bank Sta=254.3,273.8
XS Rating Curve= 0 ,0
Exp/Cntr=0.3,0.1

Type RM Length L Ch R = 1 ,14219.1 ,311.8,342.8,373.6
XS GIS Cut Line= 3
     1942882.572      355364.447     1942983.483      355562.053
     1943462.161      355563.451
#Sta/Elev= 30
       0 2123.87    19.3 2118.63    38.6 2114.76    57.9 2111.76    77.2 2109.58
   135.1 2099.47   183.3 2086.69   202.6 2083.84   221.9 2081.75   270.7  2081.5
   290.3 2079.39     300  2079.4   348.9 2081.13   358.6 2080.99   368.4 2080.16
   378.2 2079.02     388  2079.5  391.54 2080.89   397.7  2083.4   407.5 2089.21
   417.3 2094.32     427 2097.96   446.6 2101.82   485.6 2111.47   505.2 2114.67
   544.3 2119.76     554 2121.49   583.3  2127.9   632.2 2133.97   700.6 2143.52
#Mann= 3 , 0 , 0
       0      .1       0   368.4    .045       0  391.54      .1       0
Bank Sta=368.4,391.54
XS Rating Curve= 0 ,0
Exp/Cntr=0.3,0.1

Type RM Length L Ch R = 1 ,13876.3 ,181.3,194.5,207.8
XS GIS Cut Line= 2
     1942950.659       355573.65     1943072.187      356129.206
#Sta/Elev= 30
       0 2079.49    19.6 2076.98    29.4 2075.98    39.2 2075.31      49 2074.97
    78.4 2074.73   117.7 2075.02   166.7 2074.46   205.9 2074.55   235.3 2074.24
   264.7 2073.05   274.5  2072.1   283.9 2070.79   294.2 2069.64     304 2069.96
   313.8 2072.82   323.6 2079.15   343.2 2096.34     353 2104.62   362.8 2112.43
   382.4 2127.27   392.2 2133.77     402  2138.5   411.8 2142.53   431.4 2151.07
   460.8 2163.52   480.4 2172.19   500.1 2179.62   519.7 2186.67   568.7 2204.73
#Mann= 3 , 0 , 0
       0      .1       0   283.9    .045       0     304      .1       0
Bank Sta=283.9,304
XS Rating Curve= 0 ,0
Exp/Cntr=0.3,0.1

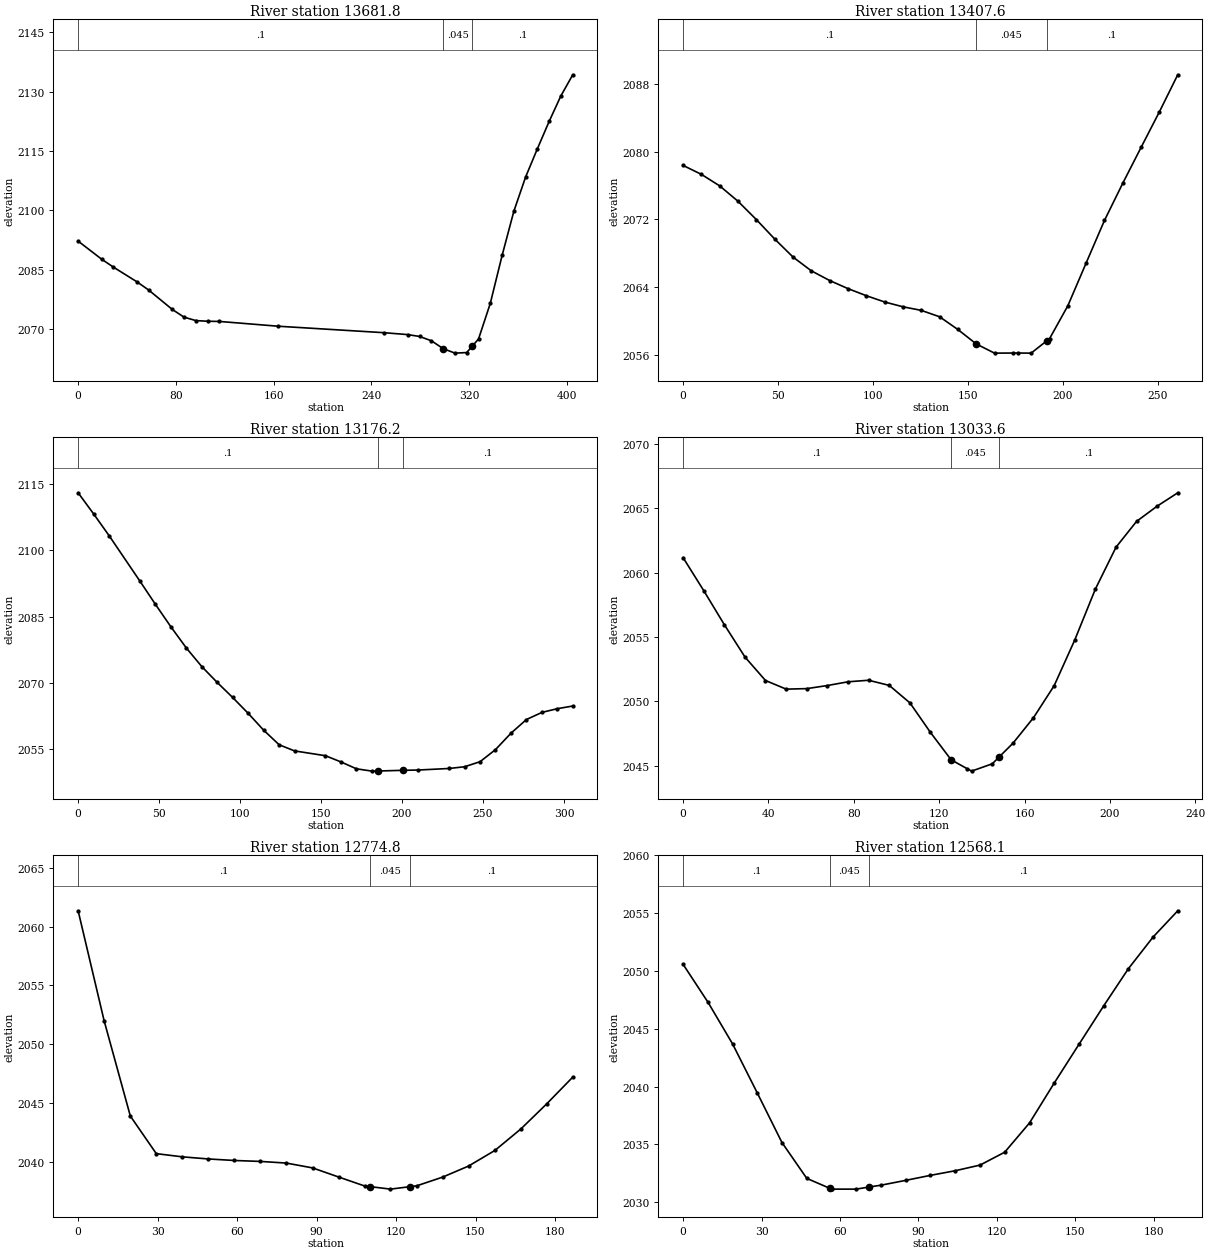
Type RM Length L Ch R = 1 ,13681.8 ,259.8,274.2,288.5
XS GIS Cut Line= 2
     1942936.625      355514.478     1942797.736      355894.686
#Sta/Elev= 28
       0  2092.2    19.3 2087.62    28.9 2085.62    48.2  2081.9    57.8 2079.82
    77.1 2074.92    86.7 2072.98    96.4 2072.11     106 2071.95   115.6  2071.9
   163.8 2070.69   250.6 2069.05   269.8 2068.57   279.5  2068.1   289.1 2067.01
   298.8 2065.02   308.4 2063.89     318 2064.03   322.6 2065.66   327.7 2067.47
   337.3 2076.44     347 2088.59   356.6 2099.75   366.2 2108.39   375.9 2115.58
   385.5 2122.47   395.1 2128.92   404.8 2134.24
#Mann= 3 , 0 , 0
       0      .1       0   298.8    .045       0   322.6      .1       0
Bank Sta=298.8,322.6
XS Rating Curve= 0 ,0
Exp/Cntr=0.3,0.1

Type RM Length L Ch R = 1 ,13407.6 ,237.2,231.4,225.8
XS GIS Cut Line= 2
     1942804.681      355516.214     1942587.667      355660.311
#Sta/Elev= 30
       0 2078.38     9.6 2077.33    19.3 2075.96    28.9 2074.15    38.6 2071.98
    48.2  2069.7    57.9 2067.56    67.5 2065.94    77.2 2064.79    86.8 2063.84
    96.5    2063   106.1 2062.26   115.8 2061.69   125.4 2061.27   135.1 2060.51
   144.7 2059.01   154.4  2057.3     164 2056.22   173.7 2056.23   176.4 2056.23
   183.3 2056.22   191.4 2057.65     193 2057.93   202.6  2061.8   212.3 2066.88
   221.9 2071.88   231.6  2076.3   241.2 2080.51   250.8 2084.69   260.5 2089.08
#Mann= 3 , 0 , 0
       0      .1       0   154.4    .045       0   191.4      .1       0
Bank Sta=154.4,191.4
XS Rating Curve= 0 ,0
Exp/Cntr=0.3,0.1

Type RM Length L Ch R = 1 ,13176.2 ,156.9,142.6,128
XS GIS Cut Line= 2
     1942660.584      355278.367     1942462.667      355511.006
#Sta/Elev= 30
       0 2113.05     9.5 2108.31    19.1 2103.36    38.2 2093.03    47.7 2087.81
    57.3  2082.7    66.8 2077.92    76.4 2073.69    85.9 2070.11    95.4 2066.72
     105 2063.12   114.5 2059.33   124.1 2056.01   133.6 2054.62   152.7 2053.53
   162.3 2052.12   171.8 2050.57   181.4 2050.04   185.4 2050.07   200.4 2050.22
     210 2050.29   229.1 2050.64   238.6 2051.03   248.2 2052.18   257.7 2054.91
   267.3 2058.64   276.8 2061.72   286.4 2063.34   295.9 2064.18   305.4 2064.78
#Mann= 3 , 0 , 0
       0      .1       0   185.4    .045       0   200.4      .1       0
Bank Sta=185.4,200.4
XS Rating Curve= 0 ,0
Exp/Cntr=0.3,0.1

Type RM Length L Ch R = 1 ,13033.6 ,267.5,258.8,250.1
XS GIS Cut Line= 2
     1942408.847      355262.742     1942388.014      355493.645
#Sta/Elev= 27
       0 2061.15     9.7 2058.58    19.3 2055.95      29 2053.43    38.6 2051.61
    48.3 2050.94      58 2050.98    67.6 2051.22    77.3 2051.51    86.9 2051.63
    96.6 2051.23   106.3 2049.87   115.9 2047.58   125.6 2045.45   133.1 2044.76
   135.2 2044.57   144.9 2045.14   148.1 2045.67   154.6 2046.74   164.2 2048.72
   173.9 2051.21   183.5 2054.74   193.2 2058.71   202.9 2061.97   212.5 2063.97
   222.2 2065.16   231.8 2066.19
#Mann= 3 , 0 , 0
       0      .1       0   125.6    .045       0   148.1      .1       0
Bank Sta=125.6,148.1
XS Rating Curve= 0 ,0
Exp/Cntr=0.3,0.1

Type RM Length L Ch R = 1 ,12774.8 ,209,206.7,204.4
XS GIS Cut Line= 2
     1942105.028      355297.464     1942158.847      355476.284
#Sta/Elev= 22
       0 2061.33     9.8 2052.01    19.7 2043.92    29.5 2040.73    39.3 2040.46
    49.1 2040.28      59 2040.15    68.8 2040.07    78.6 2039.93    88.5 2039.52
    98.3 2038.75   108.1 2037.99   110.3 2037.93   117.9 2037.72   125.3 2037.93
   127.8    2038   137.6 2038.74   147.4 2039.68   157.3    2041   167.1 2042.82
   176.9 2044.96   186.7 2047.22
#Mann= 3 , 0 , 0
       0      .1       0   110.3    .045       0   125.3      .1       0
Bank Sta=110.3,125.3
XS Rating Curve= 0 ,0
Exp/Cntr=0.3,0.1

Type RM Length L Ch R = 1 ,12568.1 ,487.3,485.7,484
XS GIS Cut Line= 2
     1941914.056      355398.159     1941985.236      355573.506
#Sta/Elev= 23
       0 2050.57     9.5  2047.3    18.9  2043.7    28.4 2039.44    37.8 2035.17
    47.3 2032.07    56.1 2031.21    56.8 2031.14    66.2 2031.14    71.1 2031.32
    75.7 2031.48    85.2  2031.9    94.6 2032.33   104.1 2032.73   113.6 2033.22
     123 2034.33   132.5 2036.86   141.9 2040.29   151.4 2043.65   160.9 2046.99
   170.3 2050.19   179.8 2052.94   189.2  2055.2
#Mann= 3 , 0 , 0
       0      .1       0    56.1    .045       0    71.1      .1       0
Bank Sta=56.1,71.1
XS Rating Curve= 0 ,0
Exp/Cntr=0.3,0.1