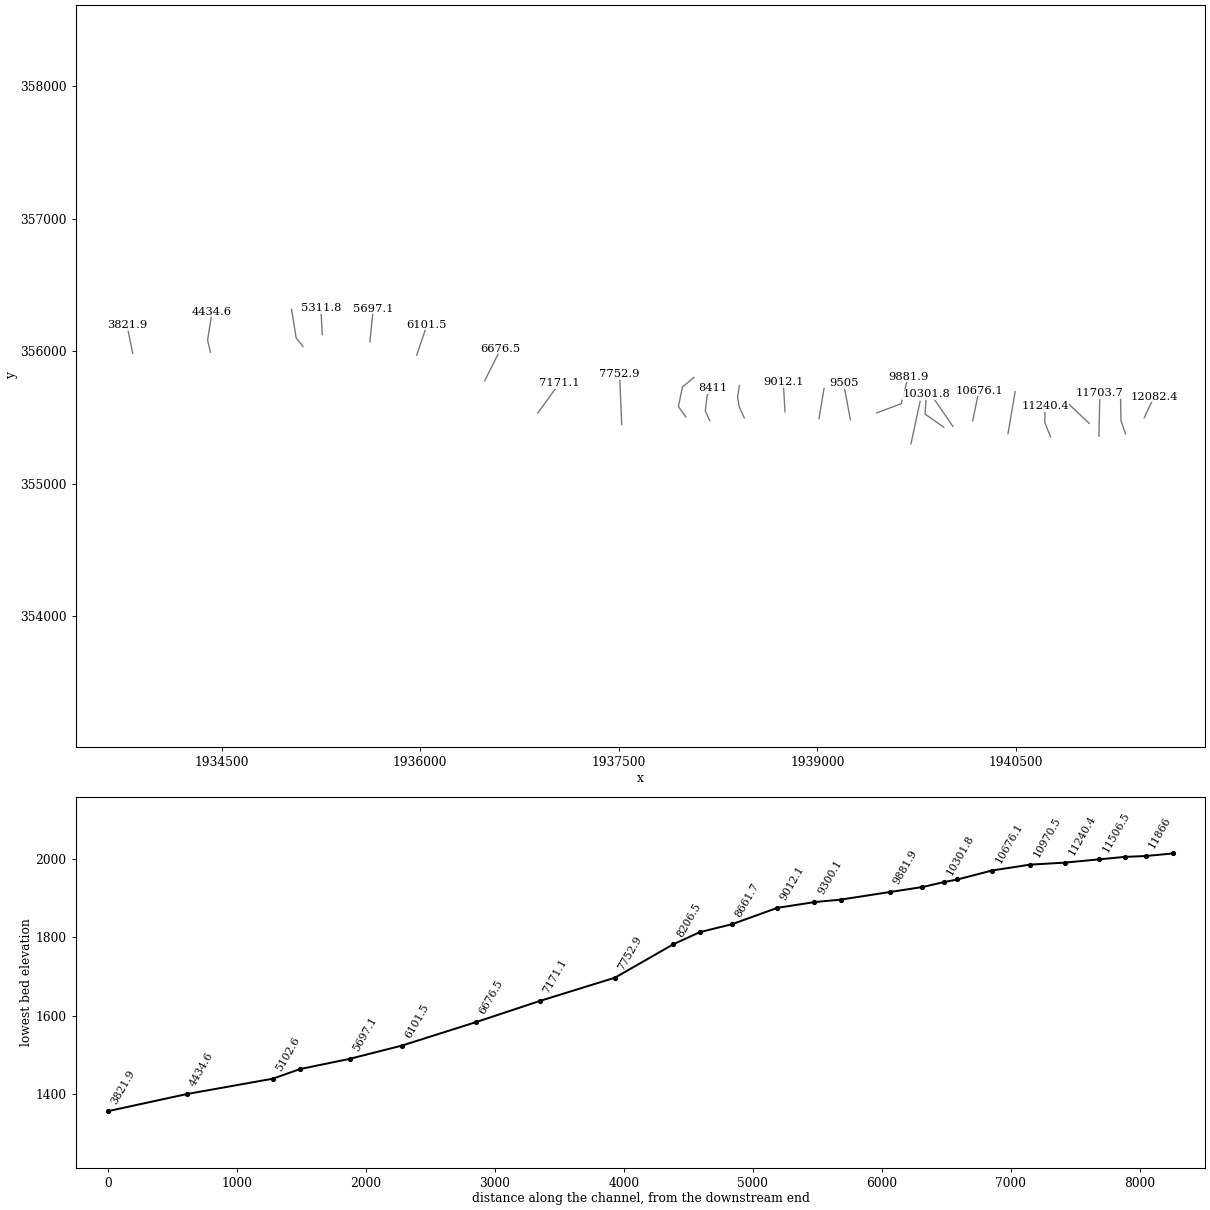
HEC-RAS study ELSEYRN.prj: ELSEYRN

--- ELSEYRN.g01 (geometry) --- (continued)

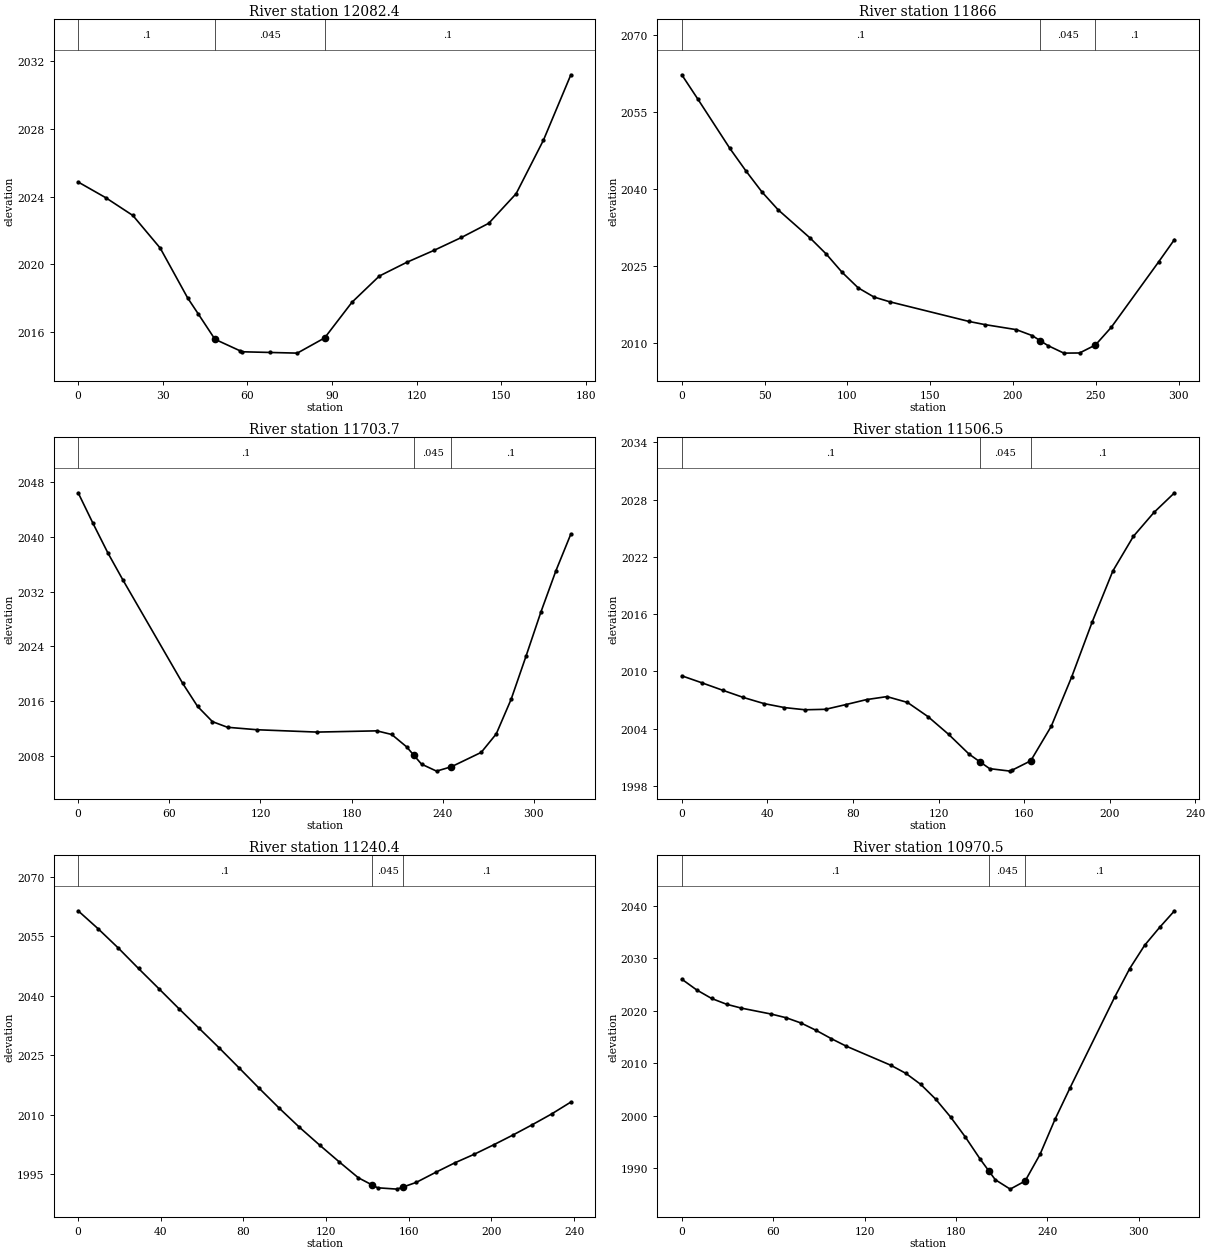
Type RM Length L Ch R = 1 ,12082.4 ,206,216.4,226.7
XS GIS Cut Line= 2
     1941469.611      355498.853     1941544.264      355656.839
#Sta/Elev= 21
       0 2024.86     9.7 2023.94    19.4 2022.88    29.1 2020.95    38.8 2018.01
    42.5 2017.08    48.5 2015.56    57.5 2014.87    58.2 2014.82      68 2014.78
    77.7 2014.74    87.4 2015.64    97.1 2017.75   106.8  2019.3   116.5 2020.11
   126.2 2020.82   135.9 2021.58   145.6 2022.42   155.3 2024.17     165 2027.34
   174.7  2031.2
#Mann= 3 , 0 , 0
       0      .1       0    48.5    .045       0    87.4      .1       0
Bank Sta=48.5,87.4
XS Rating Curve= 0 ,0
Exp/Cntr=0.3,0.1

Type RM Length L Ch R = 1 ,11866   ,163,162.3,161.5
XS GIS Cut Line= 3
     1941328.986      355377.325     1941294.264       355478.02
     1941290.792      355668.992
#Sta/Elev= 24
       0 2062.32     9.7 2057.58      29 2047.98    38.7 2043.59    48.4 2039.48
    58.1 2036.02    77.5 2030.49    87.2 2027.38    96.8 2023.81   106.5 2020.78
   116.1 2018.98   125.6 2018.06   173.4 2014.23   182.9 2013.62     202 2012.63
   211.6 2011.47   216.4 2010.48   221.1 2009.52   230.7 2008.05   240.2 2008.08
   249.8 2009.64   259.3 2013.07     288 2025.87   297.5  2030.2
#Mann= 3 , 0 , 0
       0      .1       0   216.4    .045       0   249.8      .1       0
Bank Sta=216.4,249.8
XS Rating Curve= 0 ,0
Exp/Cntr=0.3,0.1

Type RM Length L Ch R = 1 ,11703.7 ,178.2,197.2,216.5
XS GIS Cut Line= 2
     1941127.597      355359.964     1941134.976      355684.183
#Sta/Elev= 24
       0 2046.39     9.8 2041.92    19.6 2037.61    29.5 2033.67    68.8 2018.62
    78.6 2015.26    88.4 2013.04    98.3 2012.22   117.9 2011.86   157.2 2011.52
   196.6  2011.7   206.4 2011.17   216.2 2009.37   221.1 2008.11     226 2006.85
   235.9 2005.83   245.7 2006.47   265.3 2008.56   275.2 2011.25     285  2016.3
   294.8 2022.58   304.6 2029.02   314.5 2035.04   324.3 2040.38
#Mann= 3 , 0 , 0
       0      .1       0   221.1    .045       0   245.7      .1       0
Bank Sta=221.1,245.7
XS Rating Curve= 0 ,0
Exp/Cntr=0.3,0.1

Type RM Length L Ch R = 1 ,11506.5 ,286.1,266.1,245.1
XS GIS Cut Line= 2
     1941054.681      355456.318      1940887.58      355614.738
#Sta/Elev= 27
       0 2009.53     9.6 2008.78    19.2 2008.01    28.8 2007.26    38.4 2006.62
      48  2006.2    57.6 2005.97    67.2 2006.02    76.8 2006.52    86.4 2007.04
    95.9 2007.35   105.5 2006.74   115.1 2005.25   124.7  2003.4   134.3 2001.32
   139.4 2000.51   143.9  1999.8   153.5 1999.54   154.4 1999.64   163.1 2000.62
   172.7 2004.24   182.3 2009.44   191.9 2015.21   201.5 2020.52   211.1 2024.15
   220.7 2026.65   230.3 2028.71
#Mann= 3 , 0 , 0
       0      .1       0   139.4    .045       0   163.1      .1       0
Bank Sta=139.4,163.1
XS Rating Curve= 0 ,0
Exp/Cntr=0.3,0.1

Type RM Length L Ch R = 1 ,11240.4 ,272.5,269.9,267.1
XS GIS Cut Line= 3
     1940761.712      355356.492     1940718.309      355464.999
     1940720.479      355586.527
#Sta/Elev= 28
       0 2061.47     9.7 2056.92    19.5 2052.03    29.2  2046.9      39 2041.83
    48.7 2036.78    58.4 2031.85    68.2 2026.86    77.9 2021.77    87.6 2016.63
    97.4 2011.56   107.1 2006.77   116.9 2002.26   126.2  1998.1   135.6 1994.02
   142.3  1992.2   144.9  1991.5   154.3 1991.16   157.3 1991.71   163.6 1992.86
     173  1995.4   182.3 1997.81   191.7 1999.98     201 2002.34   210.4 2004.83
   219.7 2007.42   229.1 2010.15   238.4 2013.15
#Mann= 3 , 0 , 0
       0      .1       0   142.3    .045       0   157.3      .1       0
Bank Sta=142.3,157.3
XS Rating Curve= 0 ,0
Exp/Cntr=0.3,0.1

Type RM Length L Ch R = 1 ,10970.5 ,294.9,294.4,293.7
XS GIS Cut Line= 2
     1940440.531      355378.193     1940494.785      355697.204
#Sta/Elev= 30
       0 2025.99     9.8 2023.94    19.6 2022.32    29.4 2021.22    39.2 2020.48
    58.8 2019.35    68.6 2018.65    78.4 2017.64    88.2 2016.26    98.1 2014.69
   107.9 2013.26   137.3 2009.61   147.1 2008.08   156.9 2005.98   166.7 2003.18
   176.5 1999.78   186.3 1995.93   196.1  1991.7   201.9 1989.41   205.9 1987.83
   215.7 1986.04   225.5 1987.58   235.3 1992.66   245.1  1999.3     255 2005.31
   284.4 2022.62   294.2 2028.01     304 2032.44   313.8 2035.83   323.6    2039
#Mann= 3 , 0 , 0
       0      .1       0   201.9    .045       0   225.5      .1       0
Bank Sta=201.9,225.5
XS Rating Curve= 0 ,0
Exp/Cntr=0.3,0.1

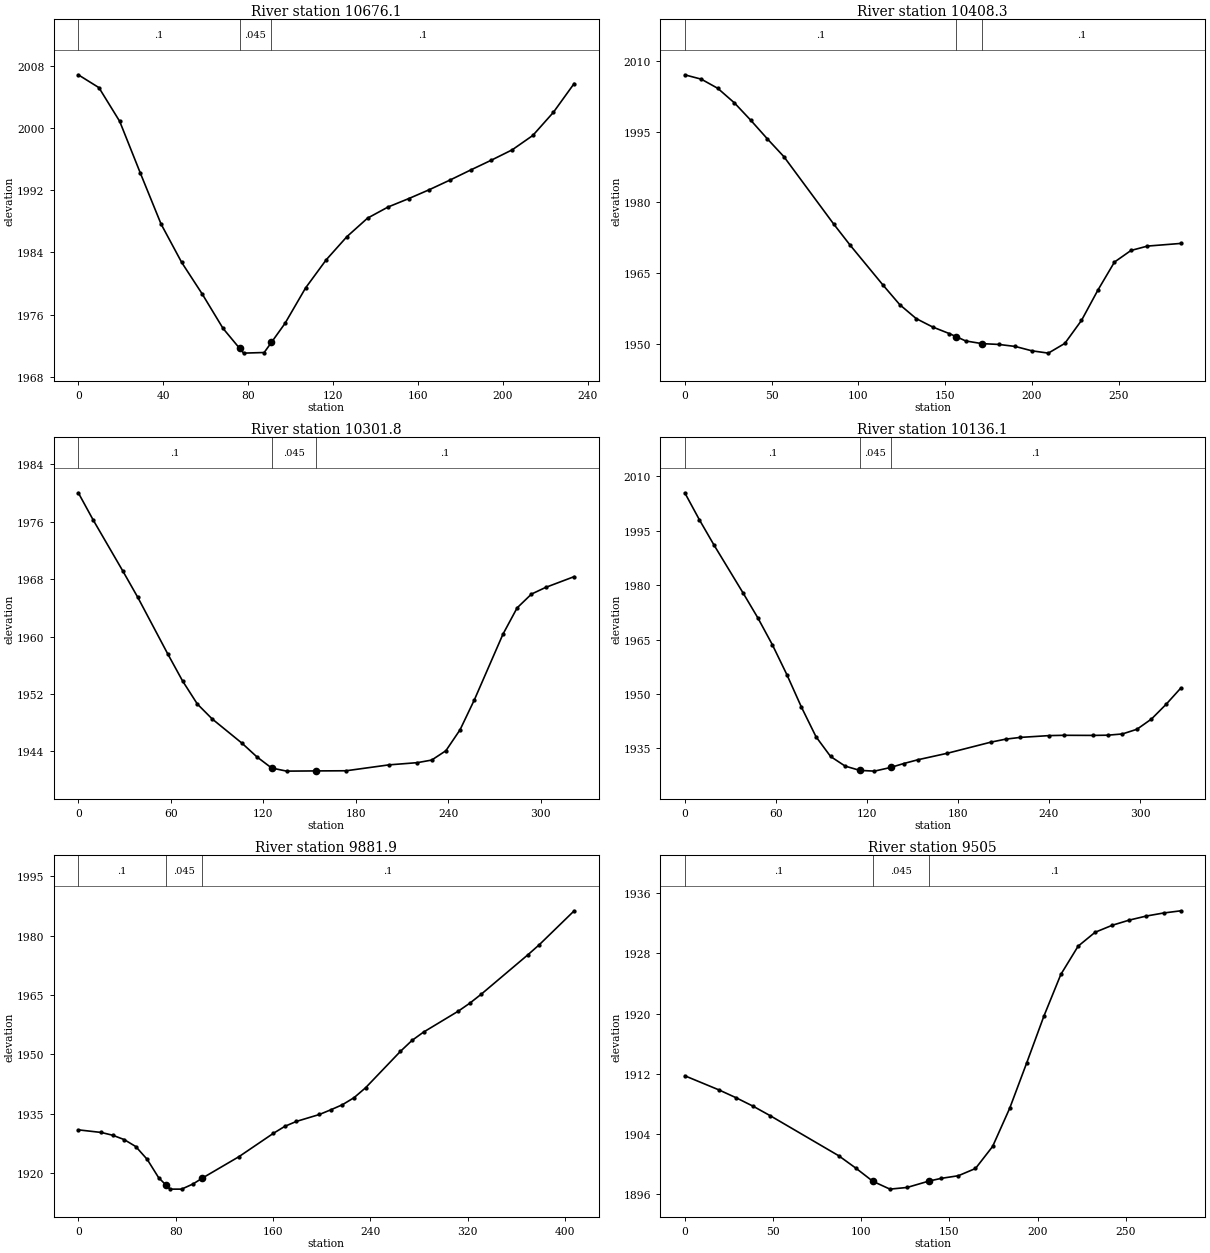
Type RM Length L Ch R = 1 ,10676.1 ,249.3,267.8,286.3
XS GIS Cut Line= 2
     1940173.733      355475.594      1940221.22      355704.398
#Sta/Elev= 27
       0  2006.9     9.7 2005.25    19.5  2000.9    29.2 1994.25      39 1987.66
    48.7 1982.72    58.4 1978.64    68.2 1974.21      76 1971.64    77.9 1971.02
    87.6  1971.1      91  1972.4    97.4 1974.85   107.1 1979.42   116.8 1983.04
   126.6 1986.04   136.3 1988.42     146 1989.86   155.8 1990.95   165.5  1992.1
   175.3 1993.35     185 1994.64   194.7  1995.9   204.5 1997.23   214.2 1999.08
   223.9 2002.06   233.7 2005.78
#Mann= 3 , 0 , 0
       0      .1       0      76    .045       0      91      .1       0
Bank Sta=76,91
XS Rating Curve= 0 ,0
Exp/Cntr=0.3,0.1

Type RM Length L Ch R = 1 ,10408.3 ,98.4,106.5,114.4
XS GIS Cut Line= 2
     1940024.107      355434.136     1939862.904      355669.862
#Sta/Elev= 28
       0 2007.03     9.5 2006.11      19 2004.17    28.6 2001.08    38.1 1997.37
    47.6 1993.45    57.1 1989.69    85.7 1975.46    95.2 1970.97   114.2 1962.49
   123.8 1958.36   133.3  1955.4   142.8 1953.62   152.3 1952.24   156.2  1951.6
   161.8 1950.67   171.2  1950.1   180.9 1949.93   190.4  1949.5   199.9 1948.58
   209.4 1948.09   218.9 1950.15   228.5 1955.02     238 1961.47   247.5 1967.38
     257 1969.83   266.5 1970.76   285.6 1971.32
#Mann= 3 , 0 , 0
       0      .1       0   156.2    .045       0   171.2      .1       0
Bank Sta=156.2,171.2
XS Rating Curve= 0 ,0
Exp/Cntr=0.3,0.1

Type RM Length L Ch R = 1 ,10301.8 ,193.7,165.7,137.2
XS GIS Cut Line= 3
     1939956.139      355427.381     1939813.995      355527.207
     1939823.761      355674.777
#Sta/Elev= 25
       0 1980.01     9.6 1976.24      29 1969.07    38.6 1965.44    57.9 1957.62
    67.6 1953.82    77.2  1950.6    86.8 1948.53   106.2 1945.14   115.8 1943.25
   125.4 1941.69   135.1 1941.26   154.4 1941.29   173.7 1941.31   201.4 1942.13
   219.9 1942.44   229.2  1942.8   238.4  1944.1   247.6 1947.02   256.9  1951.2
   275.4 1960.32   284.6 1963.99   293.9 1965.91   303.1 1966.84   321.6 1968.34
#Mann= 3 , 0 , 0
       0      .1       0   125.4    .045       0   154.4      .1       0
Bank Sta=125.4,154.4
XS Rating Curve= 0 ,0
Exp/Cntr=0.3,0.1

Type RM Length L Ch R = 1 ,10136.1 ,277.1,254.3,231.4
XS GIS Cut Line= 2
      1939707.49      355302.912     1939776.563      355622.374
#Sta/Elev= 29
       0 2005.41     9.6    1998    19.2 1991.06    38.4 1977.83    48.1 1970.99
    57.7 1963.57    67.3  1955.3    76.9 1946.35    86.5  1938.2    96.1 1932.77
   105.7 1930.12   115.4 1928.94     125 1928.74   135.6 1929.74   144.2 1930.82
   153.8 1931.89     173 1933.66   201.9 1936.74   211.5 1937.55   221.1 1938.03
   240.3 1938.53   249.9 1938.61   269.2 1938.58   278.8 1938.64   288.4 1938.98
     298 1940.27   307.6  1943.1   317.2 1947.13   326.8 1951.57
#Mann= 3 , 0 , 0
       0      .1       0   115.4    .045       0   135.6      .1       0
Bank Sta=115.4,135.6
XS Rating Curve= 0 ,0
Exp/Cntr=0.3,0.1

Type RM Length L Ch R = 1 ,9881.9  ,344.6,376.8,409.1
XS GIS Cut Line= 3
     1939448.466      355536.033       1939634.1      355605.106
     1939685.905      355808.008
#Sta/Elev= 30
       0  1930.9    18.9 1930.24    28.3 1929.53    37.7 1928.44    47.2 1926.68
    56.6 1923.44      66 1918.81   71.831917.018    75.4 1915.92    84.9 1915.92
    94.3 1917.23     102 1918.72     132 1924.12   160.3 1930.02   169.8  1931.8
   179.2 1933.03   198.1 1934.78   207.6 1935.98   217.1 1937.26   226.6 1939.03
   236.1 1941.54   264.7 1950.73   274.2 1953.49   283.7  1955.6   312.3  1960.9
   321.8 1962.92   331.3 1965.22   369.4 1975.12   378.9  1977.7   407.5 1986.25
#Mann= 3 , 0 , 0
       0      .1       0   71.83    .045       0     102      .1       0
Bank Sta=71.83,102
XS Rating Curve= 0 ,0
Exp/Cntr=0.3,0.1

Type RM Length L Ch R = 1 ,9505    ,212.9,204.9,197
XS GIS Cut Line= 2
     1939249.881      355484.228     1939198.077       355760.52
#Sta/Elev= 26
       0 1911.75    19.4 1909.87    29.1 1908.83    38.8  1907.7    48.5 1906.44
    87.2 1901.14    96.9  1899.5   106.6 1897.74   116.3  1896.7     126 1896.92
   138.4 1897.77   145.4 1898.13   155.1 1898.48   164.8 1899.44   174.5 1902.36
   184.2 1907.44   193.9  1913.5   203.6 1919.68   213.2 1925.21     223 1928.96
   232.6  1930.8   242.3 1931.73     252 1932.42   261.7 1932.96   271.4 1933.36
   281.1 1933.65
#Mann= 3 , 0 , 0
       0      .1       0   106.6    .045       0   138.4      .1       0
Bank Sta=106.6,138.4
XS Rating Curve= 0 ,0
Exp/Cntr=0.3,0.1

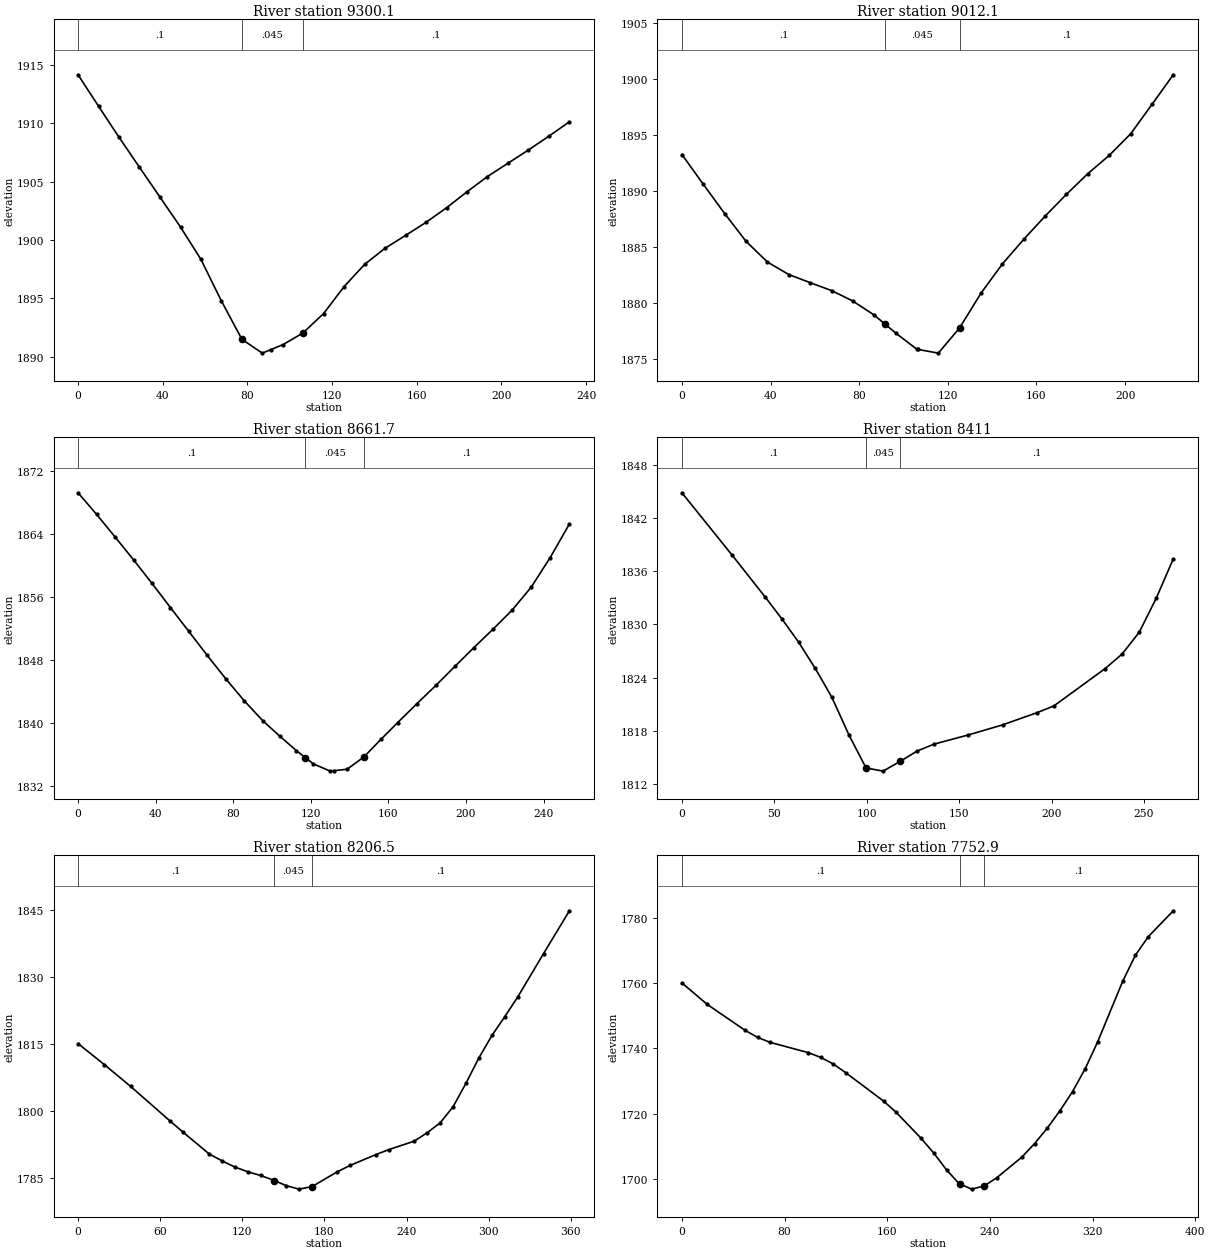
Type RM Length L Ch R = 1 ,9300.1  ,282.4,288,292.8
XS GIS Cut Line= 2
     1939012.443      355492.862     1939051.297      355721.667
#Sta/Elev= 26
       0 1914.13     9.7 1911.43    19.3  1908.8      29 1906.22    38.7 1903.66
    48.4  1901.1      58 1898.35    67.7 1894.78    77.4  1891.5      87 1890.32
    91.2 1890.63    96.7 1891.04   106.2 1892.04     116 1893.71   125.7 1896.02
   135.4 1897.92     145 1899.29   154.7 1900.39   164.4 1901.51   174.1 1902.76
   183.7 1904.12   193.4 1905.43   203.1 1906.57   212.7 1907.69   222.4 1908.88
   232.1 1910.11
#Mann= 3 , 0 , 0
       0      .1       0    77.4    .045       0   106.2      .1       0
Bank Sta=77.4,106.2
XS Rating Curve= 0 ,0
Exp/Cntr=0.3,0.1

Type RM Length L Ch R = 1 ,9012.1  ,348.1,350.4,352.5
XS GIS Cut Line= 2
     1938755.868      355544.496     1938742.847       355765.85
#Sta/Elev= 26
       0 1893.24     9.6  1890.6    19.3 1887.97    28.9 1885.51    38.6 1883.65
    48.2 1882.54    57.8 1881.82    67.5 1881.11    77.1 1880.18    86.8 1878.92
    91.5 1878.14    96.4 1877.33     106 1875.88   106.5 1875.86   115.7 1875.53
   125.3 1877.78     135 1880.89   144.6 1883.48   154.2 1885.67   163.9 1887.75
   173.5 1889.69   183.2 1891.54   192.8 1893.16   202.5 1895.09   212.1 1897.71
   221.7 1900.35
#Mann= 3 , 0 , 0
       0      .1       0    91.5    .045       0   125.3      .1       0
Bank Sta=91.5,125.3
XS Rating Curve= 0 ,0
Exp/Cntr=0.3,0.1

Type RM Length L Ch R = 1 ,8661.7  ,257,250.7,244.4
XS GIS Cut Line= 4
     1938447.708      355498.923     1938408.645      355585.728
     1938397.686      355654.463     1938410.816      355741.978
#Sta/Elev= 30
       0 1869.23     9.5  1866.5      19 1863.64    28.6 1860.71    38.1 1857.72
    47.6 1854.65    57.1 1851.61    66.6 1848.56    76.2 1845.58    85.7 1842.79
    95.2 1840.27   103.9 1838.32   112.6 1836.45   117.1 1835.59   121.3 1834.78
     130 1833.86   132.1 1833.92   138.7  1834.1   147.4 1835.67   156.1 1837.89
   164.8 1840.04   174.6 1842.41   184.5 1844.76   194.3 1847.18   204.1 1849.57
     214 1851.92   223.8 1854.33   233.6 1857.24   243.4    1861   253.3 1865.27
#Mann= 3 , 0 , 0
       0      .1       0   117.1    .045       0   147.4      .1       0
Bank Sta=117.1,147.4
XS Rating Curve= 0 ,0
Exp/Cntr=0.3,0.1

Type RM Length L Ch R = 1 ,8411    ,206.4,204.5,202.6
XS GIS Cut Line= 4
     1938187.291      355477.221     1938153.858       355551.11
     1938167.886      355670.349     1938208.993      355720.277
#Sta/Elev= 22
       0 1844.83      27 1837.85    45.1 1833.08    54.1 1830.62    63.1 1828.02
    72.1 1825.06    81.1  1821.8    90.3 1817.58    99.6 1813.84   108.8 1813.48
     118 1814.57   127.3 1815.75   136.5 1816.53     155 1817.56   173.5 1818.69
   191.9 1820.05   201.2 1820.82   228.9 1825.02   238.1 1826.66   247.4 1829.12
   256.6 1832.95   265.8 1837.37
#Mann= 3 , 0 , 0
       0      .1       0    99.6    .045       0     118      .1       0
Bank Sta=99.6,118
XS Rating Curve= 0 ,0
Exp/Cntr=0.3,0.1

Type RM Length L Ch R = 1 ,8206.5  ,448.1,453.7,459.2
XS GIS Cut Line= 4
     1938006.568      355505.814     1937950.446      355583.521
     1937980.665      355730.301     1938067.007      355803.691
#Sta/Elev= 29
       0 1815.12    19.2 1810.42    38.3 1805.56    67.1 1797.81    76.7 1795.28
    95.8  1790.4   105.2 1788.85   114.6 1787.46     124 1786.41   133.3 1785.58
   143.5 1784.45     152  1783.3   161.4 1782.52   170.8 1783.06   189.5 1786.43
   198.9 1787.85   217.6 1790.26     227 1791.37   245.7 1793.28   255.2 1795.18
   264.6 1797.38     274 1800.97   283.5 1806.28   292.9 1811.94   302.4 1816.95
   311.8 1821.17   321.3  1825.6   340.1 1835.29     359 1844.88
#Mann= 3 , 0 , 0
       0      .1       0   143.5    .045       0   170.8      .1       0
Bank Sta=143.5,170.8
XS Rating Curve= 0 ,0
Exp/Cntr=0.3,0.1

Type RM Length L Ch R = 1 ,7752.9  ,597,581.8,566.5
XS GIS Cut Line= 2
     1937522.219       355447.05     1937505.789      355829.593
#Sta/Elev= 30
       0 1760.03    19.6  1753.5    49.1 1745.56    58.9 1743.39    68.7 1741.85
    98.2 1738.74     108 1737.28   117.8 1735.27   127.6 1732.59   157.1  1723.9
   166.9 1720.47   186.5 1712.46   196.4 1707.92   206.2 1702.85     216 1698.64
   217.1 1698.45   225.8 1696.95   235.6 1697.92   245.4 1700.44   265.1  1706.8
   274.9  1710.9   284.7  1715.6   294.5 1720.85   304.4 1726.77   314.2 1733.71
     324    1742   343.6 1760.61   353.4 1768.49   363.3 1774.11   382.9 1782.09
#Mann= 3 , 0 , 0
       0      .1       0   217.1    .045       0   235.6      .1       0
Bank Sta=217.1,235.6
XS Rating Curve= 0 ,0
Exp/Cntr=0.3,0.1

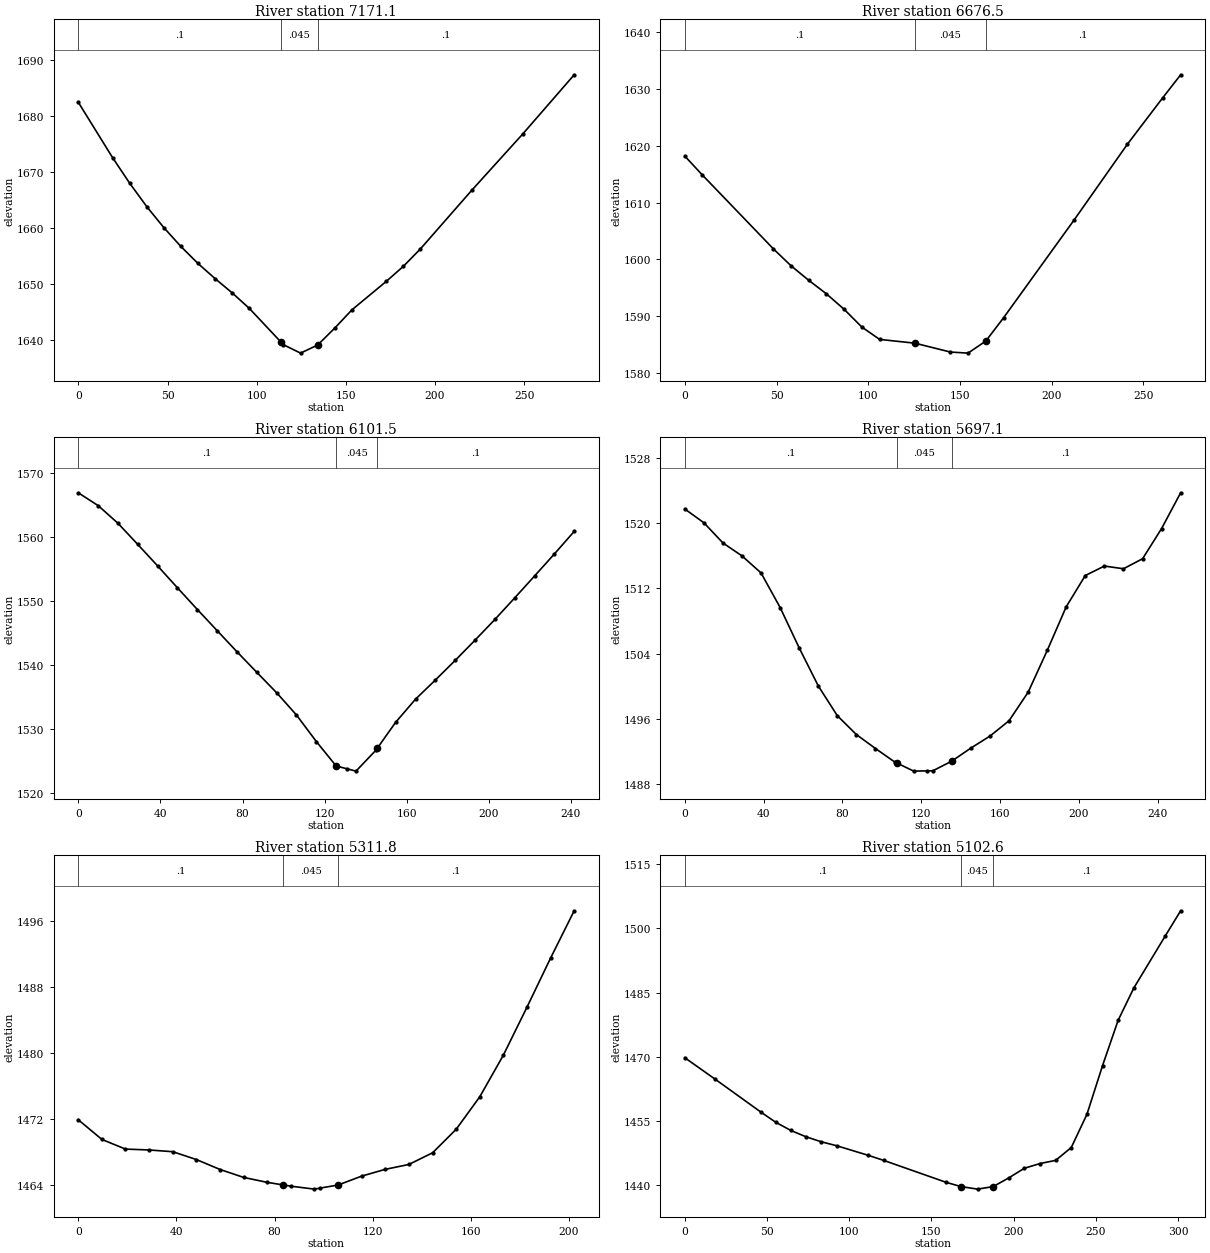
Type RM Length L Ch R = 1 ,7171.1  ,490.8,494.5,498.1
XS GIS Cut Line= 2
     1936888.449      355536.033     1937052.497       355760.52
#Sta/Elev= 22
       0 1682.37    19.2 1672.49    28.8 1667.92    38.4 1663.73    47.9 1660.01
    57.5 1656.63    67.1 1653.59    76.7 1650.88    86.3 1648.33    95.9 1645.56
   113.5 1639.59     115 1639.08   124.6 1637.58   134.2 1639.03   143.8 1642.06
   153.4 1645.31   172.6 1650.38   182.2 1653.07   191.8 1656.19   220.5 1666.63
   249.3 1676.76     278 1687.28
#Mann= 3 , 0 , 0
       0      .1       0   113.5    .045       0   134.2      .1       0
Bank Sta=113.5,134.2
XS Rating Curve= 0 ,0
Exp/Cntr=0.3,0.1

Type RM Length L Ch R = 1 ,6676.5  ,571.5,575.1,577.9
XS GIS Cut Line= 2
     1936486.962      355777.788      1936607.84      356019.544
#Sta/Elev= 18
       0 1618.22     9.6 1614.88    48.3 1601.87    57.9  1598.9    67.6 1596.32
    77.2 1593.95    86.9 1591.21    96.5  1588.1   106.2 1585.92   125.5 1585.25
   144.8 1583.69   154.4  1583.5   164.1 1585.63   173.8 1589.74   212.4 1607.04
   241.3 1620.32   260.6 1628.52   270.3 1632.54
#Mann= 3 , 0 , 0
       0      .1       0   125.5    .045       0   164.1      .1       0
Bank Sta=125.5,164.1
XS Rating Curve= 0 ,0
Exp/Cntr=0.3,0.1

Type RM Length L Ch R = 1 ,6101.5  ,399.3,404.4,409.5
XS GIS Cut Line= 2
     1935973.232      355972.056     1936050.939      356200.861
#Sta/Elev= 28
       0 1566.84     9.7 1564.84    19.3  1562.1      29 1558.79    38.7 1555.43
    48.3 1552.04      58 1548.66    67.7 1545.35    77.3 1542.08      87 1538.86
    96.7 1535.67   106.3 1532.22     116 1528.08   125.6 1524.29   130.7 1523.86
   135.3 1523.48     145 1526.74   145.7 1527.06   154.6 1531.08   164.3 1534.69
     174 1537.68   183.6 1540.72   193.3 1543.88     203 1547.12   212.6 1550.46
   222.3 1553.88     232 1557.33   241.6 1560.82
#Mann= 3 , 0 , 0
       0      .1       0   125.6    .045       0   145.7      .1       0
Bank Sta=125.6,145.7
XS Rating Curve= 0 ,0
Exp/Cntr=0.3,0.1

Type RM Length L Ch R = 1 ,5697.1  ,381.1,385.3,389.3
XS GIS Cut Line= 2
     1935619.233      356071.349     1935645.135      356321.738
#Sta/Elev= 29
       0 1521.73     9.7 1520.04    19.4 1517.56      29 1515.99    38.7  1513.9
    48.4 1509.66    58.1  1504.7    67.8 1500.04    77.4 1496.42    87.1  1494.1
    96.8 1492.39   106.5 1490.75   107.8  1490.6   116.2 1489.62   122.8 1489.65
   125.9 1489.66   135.5 1490.84   145.2 1492.44   154.9 1493.91   164.6 1495.79
   174.3 1499.29     184 1504.41   193.6 1509.74   203.3 1513.58     213 1514.74
   222.7 1514.41   232.4 1515.64     242 1519.32   251.7 1523.71
#Mann= 3 , 0 , 0
       0      .1       0   107.8    .045       0   135.5      .1       0
Bank Sta=107.8,135.5
XS Rating Curve= 0 ,0
Exp/Cntr=0.3,0.1

Type RM Length L Ch R = 1 ,5311.8  ,206.7,209.2,211.4
XS GIS Cut Line= 2
     1935259.774      356126.093     1935248.923      356327.916
#Sta/Elev= 24
       0 1471.87     9.6 1469.49    19.2 1468.32    28.9 1468.21    38.5    1468
    48.1 1467.05    57.8 1465.84    67.4 1464.88      77 1464.28    83.5 1463.97
    86.6 1463.82    96.2 1463.46    98.5 1463.58   105.9 1463.96   115.5 1465.04
   125.1 1465.86   134.7 1466.45   144.4 1467.87     154 1470.72   163.6 1474.65
   173.2 1479.69   182.9 1485.56   192.5  1491.5   202.1 1497.23
#Mann= 3 , 0 , 0
       0      .1       0    83.5    .045       0   105.9      .1       0
Bank Sta=83.5,105.9
XS Rating Curve= 0 ,0
Exp/Cntr=0.3,0.1

Type RM Length L Ch R = 1 ,5102.6  ,675.1,668,661
XS GIS Cut Line= 3
     1935114.136      356036.812     1935062.332      356101.568
     1935027.795      356317.421
#Sta/Elev= 25
       0 1469.73    18.4 1464.72    46.1 1457.05    55.3 1454.62    64.5  1452.7
    73.7 1451.23    82.9 1450.06    92.4 1449.12   111.4  1446.9     121 1445.69
     159 1440.55   167.8 1439.58     178 1438.97   187.5 1439.56     197  1441.6
   206.5 1443.86     216 1444.96   225.5  1445.7     235 1448.71   244.5 1456.45
     254 1467.86   263.5 1478.49     273 1486.03     292 1498.14   301.5 1504.12
#Mann= 3 , 0 , 0
       0      .1       0   167.8    .045       0   187.5      .1       0
Bank Sta=167.8,187.5
XS Rating Curve= 0 ,0
Exp/Cntr=0.3,0.1

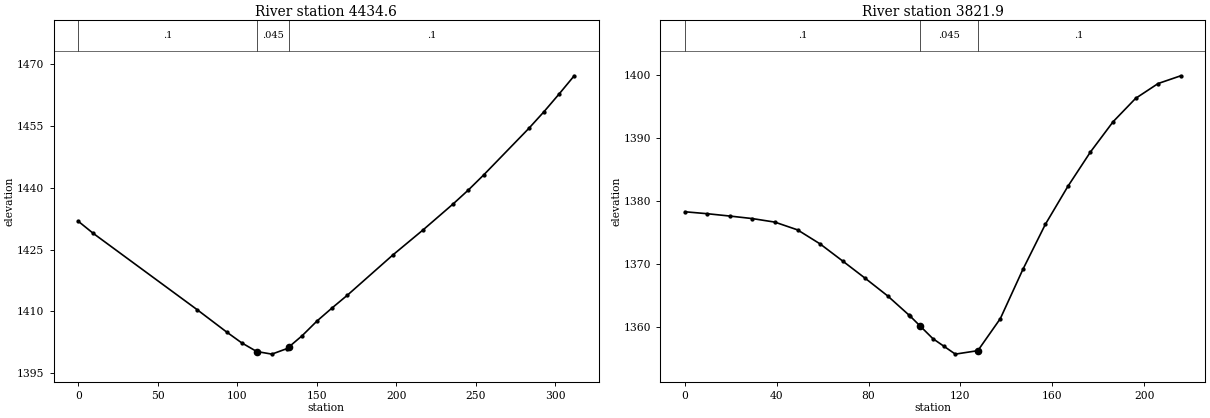
Type RM Length L Ch R = 1 ,4434.6  ,604.6,612.7,620.8
XS GIS Cut Line= 3
     1934414.772      355993.642     1934393.187        356084.3
     1934427.724      356300.153
#Sta/Elev= 22
       0 1431.85     9.3 1428.95    74.6 1410.46    93.2 1405.03   102.7 1402.39
   112.2 1400.28   121.7 1399.65   131.2 1400.99   132.7 1401.48   140.7  1404.1
   150.2 1407.72   159.7 1410.89   169.2 1413.94   197.7 1423.66   216.8 1429.77
   235.8  1436.1   245.3 1439.45   254.8 1443.05   283.3 1454.38   292.8 1458.41
   302.3  1462.7   311.8 1467.12
#Mann= 3 , 0 , 0
       0      .1       0   112.2    .045       0   132.7      .1       0
Bank Sta=112.2,132.7
XS Rating Curve= 0 ,0
Exp/Cntr=0.3,0.1

Type RM Length L Ch R = 1 ,3821.9  ,535.1,513.9,492.5
XS GIS Cut Line= 2
     1933827.652      355985.007     1933784.481      356196.543
#Sta/Elev= 26
       0 1378.33     9.8 1378.02    19.6 1377.65    29.4 1377.25    39.2 1376.69
    49.1 1375.46    58.9 1373.24    68.7 1370.54    78.5 1367.81    88.3 1365.01
    97.7 1361.94    98.1 1361.81  102.461360.238     108 1358.24   112.7 1357.06
   117.8 1355.78   127.6 1356.33   137.4 1361.41   147.2 1369.19     157 1376.34
   166.8 1382.35   176.6 1387.78   186.5 1392.59   196.3 1396.29   206.1 1398.64
   215.9 1399.86
#Mann= 3 , 0 , 0
       0      .1       0  102.46    .045       0   127.6      .1       0
Bank Sta=102.46,127.6
XS Rating Curve= 0 ,0
Exp/Cntr=0.3,0.1