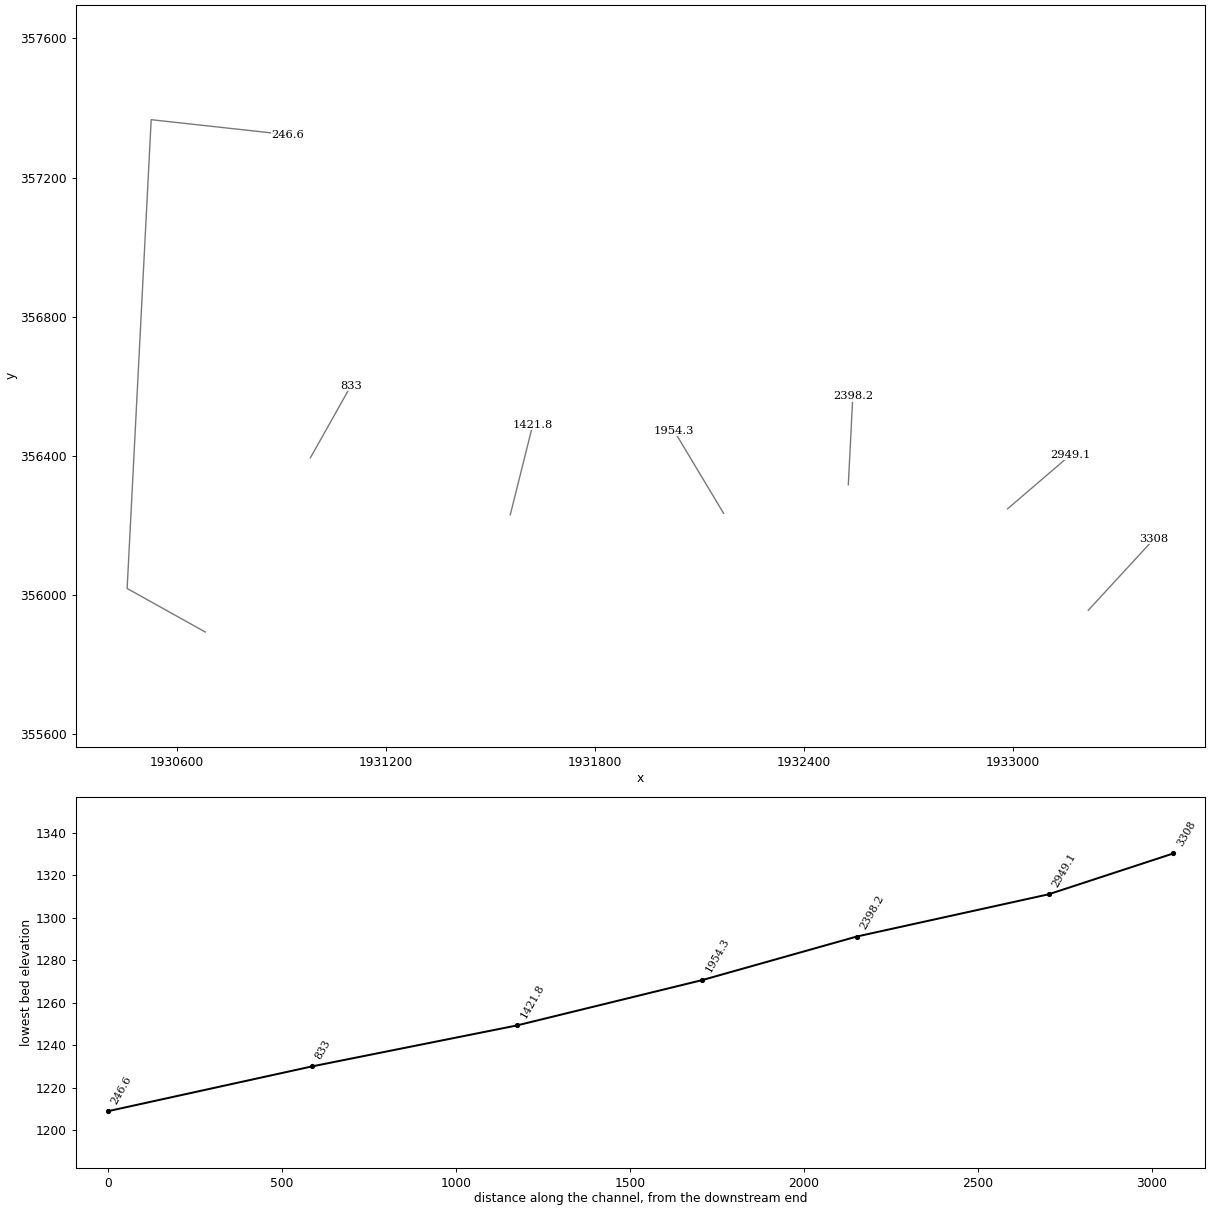
HEC-RAS study ELSEYRN.prj: ELSEYRN

--- ELSEYRN.g01 (geometry) --- (continued)

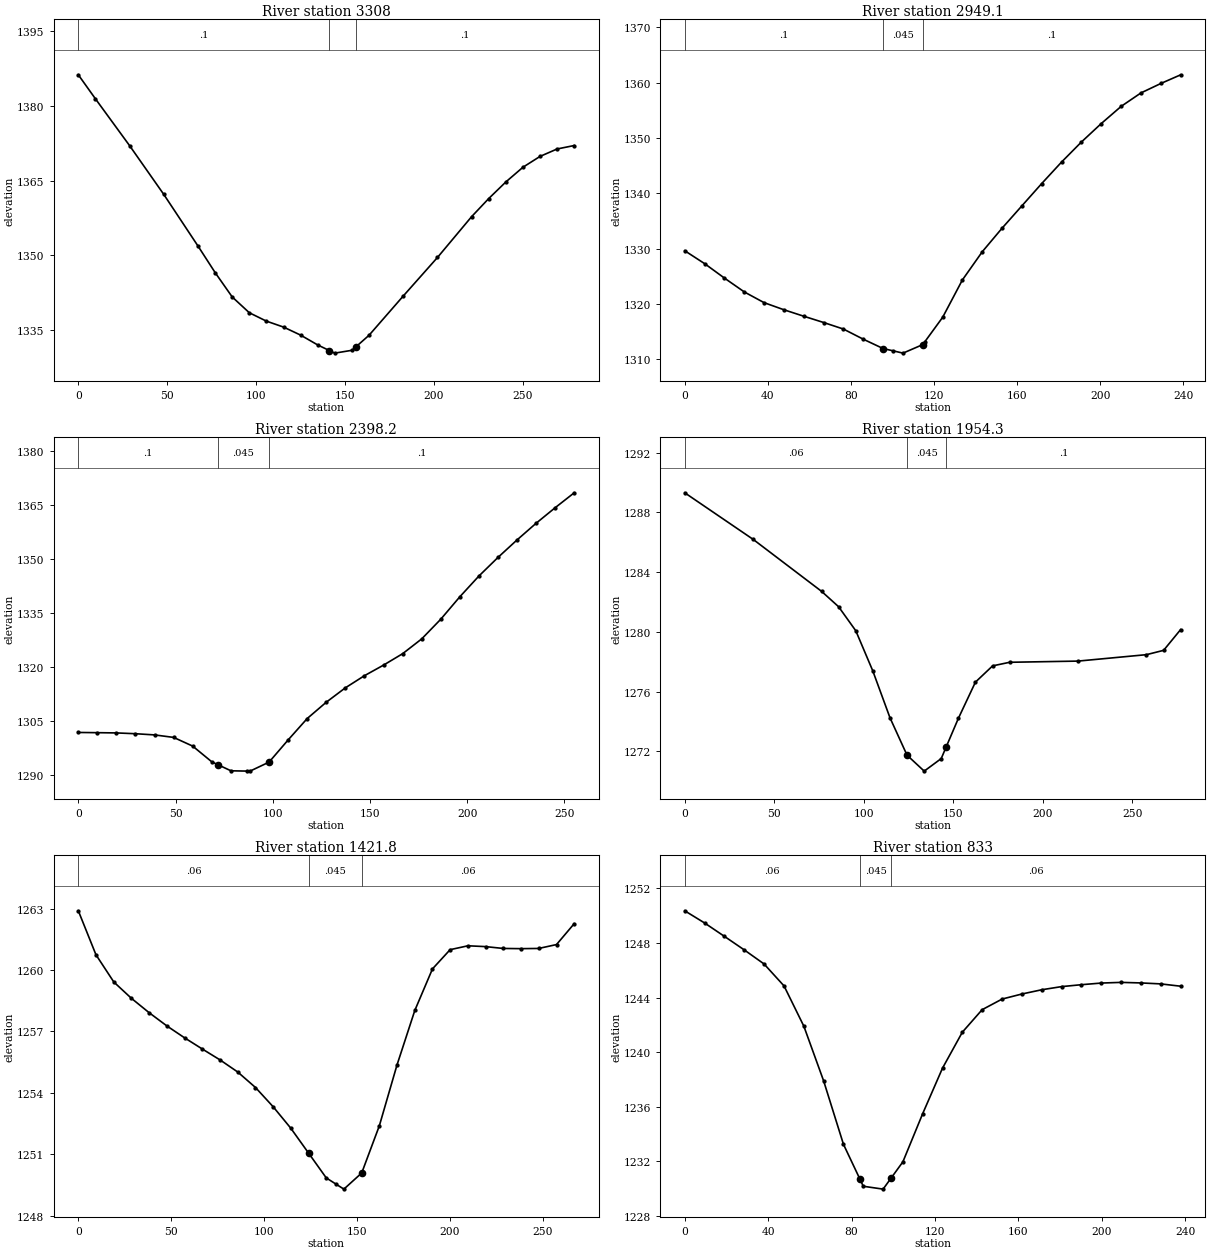
Type RM Length L Ch R = 1 ,3308    ,361.6,358.9,356.2
XS GIS Cut Line= 2
     1933217.673      355956.822     1933406.773       356162.03
#Sta/Elev= 26
       0  1386.2     9.6  1381.4    28.9 1371.97    48.1 1362.21    67.4 1351.83
      77 1346.53    86.6 1341.65    96.2 1338.49   105.8 1336.81   115.5 1335.61
   125.1    1334   134.7 1332.03   141.3  1330.9   144.3 1330.39     154 1330.96
   156.3 1331.68   163.6 1333.98   182.8 1341.83   202.1 1349.58   221.3 1357.76
   230.9 1361.38   240.6 1364.73   250.2 1367.67   259.8 1369.84   269.4 1371.33
     279 1372.02
#Mann= 3 , 0 , 0
       0      .1       0   141.3    .045       0   156.3      .1       0
Bank Sta=141.3,156.3
XS Rating Curve= 0 ,0
Exp/Cntr=0.3,0.1

Type RM Length L Ch R = 1 ,2949.1  ,532.1,550.9,569.4
XS GIS Cut Line= 2
     1932985.825      356248.348     1933167.142      356403.762
#Sta/Elev= 28
       0  1329.6     9.6 1327.26    19.1 1324.66    28.7 1322.15    38.2 1320.22
    47.8 1318.93    57.3 1317.77    66.9 1316.63    76.4 1315.45      86 1313.61
    95.5 1311.93   100.5  1311.5   105.1  1311.1   114.6 1312.64   115.5  1313.1
   124.2 1317.58   133.7 1324.33   143.3 1329.44   152.8 1333.68   162.4 1337.74
   171.9 1341.75   181.5 1345.65     191 1349.25   200.6  1352.6   210.2 1355.71
   219.7 1358.13   229.3 1359.84   238.8  1361.4
#Mann= 3 , 0 , 0
       0      .1       0    95.5    .045       0   114.6      .1       0
Bank Sta=95.5,114.6
XS Rating Curve= 0 ,0
Exp/Cntr=0.3,0.1

Type RM Length L Ch R = 1 ,2398.2  ,430.4,443.9,457.2
XS GIS Cut Line= 2
     1932528.217      356317.421     1932541.168      356572.128
#Sta/Elev= 29
       0 1301.92     9.8 1301.86    19.6 1301.79    29.4 1301.57    39.2 1301.24
      49 1300.55    58.8 1298.14    68.7 1293.75    71.7    1293    78.5 1291.29
    86.7 1291.21    88.3  1291.2    98.1  1293.7   107.9 1299.85   117.7 1305.78
   127.5  1310.3   137.3 1314.28   147.1 1317.64     157  1320.6   166.8 1323.76
   176.6 1327.86   186.4 1333.31   196.2 1339.53     206 1345.28   215.8 1350.43
   225.6 1355.28   235.4  1359.9   245.2 1364.21     255 1368.35
#Mann= 3 , 0 , 0
       0      .1       0    71.7    .045       0    98.1      .1       0
Bank Sta=71.7,98.1
XS Rating Curve= 0 ,0
Exp/Cntr=0.3,0.1

Type RM Length L Ch R = 1 ,1954.3  ,550.3,532.5,514.7
XS GIS Cut Line= 2
       1932169.9      356235.397     1932027.437      356472.835
#Sta/Elev= 19
       0 1289.31    38.2 1286.19    76.4 1282.71    85.9 1281.68    95.5 1280.07
     105 1277.38   114.6 1274.24   124.1 1271.74   133.7 1270.67   143.2 1271.51
   145.9 1272.27   152.8 1274.21   162.3 1276.63   171.9 1277.72   181.4 1277.96
   219.6 1278.04   257.8 1278.47   267.4 1278.76   276.9 1280.15
#Mann= 3 , 0 , 0
       0     .06       0   124.1    .045       0   145.9      .1       0
Bank Sta=124.1,145.9
XS Rating Curve= 0 ,0
Exp/Cntr=0.3,0.1

Type RM Length L Ch R = 1 ,1421.8  ,594.8,588.8,582.5
XS GIS Cut Line= 2
     1931556.878       356231.08     1931621.634      356490.104
#Sta/Elev= 30
       0  1262.9     9.5 1260.75    19.1 1259.42    28.6 1258.62    38.1 1257.92
    47.7 1257.27    57.2 1256.69    66.8 1256.14    76.3 1255.61    85.8 1255.02
    95.4 1254.26   104.9 1253.32   114.4 1252.27     124 1251.05   133.5 1249.84
     139 1249.52     143 1249.29   152.6 1250.08   162.1 1252.39   171.6 1255.36
   181.2 1258.03   190.7 1260.06   200.2    1261   209.8 1261.19   219.3 1261.15
   228.8 1261.06   238.4 1261.05   247.9 1261.06   257.5 1261.25     267 1262.27
#Mann= 3 , 0 , 0
       0     .06       0     124    .045       0   152.6     .06       0
Bank Sta=124,152.6
XS Rating Curve= 0 ,0
Exp/Cntr=0.3,0.1

Type RM Length L Ch R = 1 ,833     ,577.7,586.4,595.5
XS GIS Cut Line= 2
     1930982.708      356395.128     1931099.269      356602.347
#Sta/Elev= 28
       0 1250.35     9.5 1249.46      19 1248.48    28.5 1247.49      38 1246.46
    47.6 1244.85    57.1  1241.9    66.6 1237.89    76.1 1233.25      84  1230.7
    85.6 1230.18    95.1 1229.97      99 1230.79   104.6 1231.97   114.1  1235.5
   123.6 1238.83   133.1 1241.46   142.6 1243.11   152.2 1243.89   161.7 1244.26
   171.2 1244.57   180.7  1244.8   190.2 1244.94   199.7 1245.06   209.2 1245.11
   218.7 1245.07   228.2    1245   237.8 1244.83
#Mann= 3 , 0 , 0
       0     .06       0      84    .045       0      99     .06       0
Bank Sta=84,99
XS Rating Curve= 0 ,0
Exp/Cntr=0.3,0.1

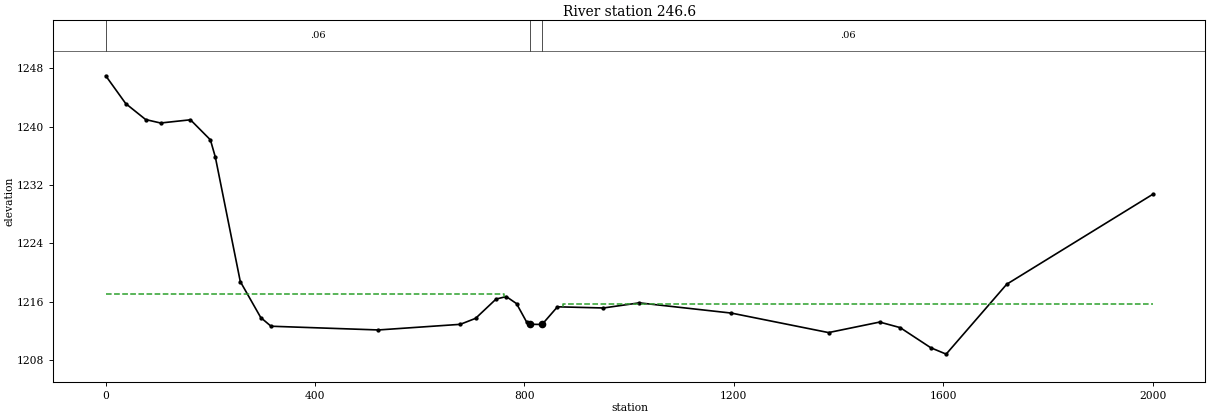
Type RM Length L Ch R = 1 ,246.6   ,245.4,246.6,247.4
XS GIS Cut Line= 4
     1930680.514      355894.349     1930456.027      356019.544
       1930525.1      357366.467     1930917.953      357323.297
#Sta/Elev= 30
       0 1246.96    38.1 1243.16    76.2 1240.97   104.7  1240.5   161.8 1240.94
   199.9 1238.19   209.4 1235.81     257 1218.79   296.1 1213.86   315.7 1212.67
   520.9 1212.16   677.3 1212.93   706.6 1213.75   745.7 1216.39   765.2 1216.73
   784.8 1215.77   804.3 1213.22   810.3 1212.94   833.6 1212.91     863 1215.33
   950.9 1215.17  1019.3 1215.87  1195.3 1214.47    1381  1211.8  1478.7 1213.24
  1517.8 1212.48  1576.4 1209.72  1605.7 1208.85  1721.4 1218.42    2001 1230.76
#Mann= 3 , 0 , 0
       0     .06       0   810.3    .045       0   833.6     .06       0
#XS Ineff= 2 , 0
          760.56 1217.03  873.24         1215.66
Permanent Ineff=
       F       F
Bank Sta=810.3,833.6
XS Rating Curve= 0 ,0
Exp/Cntr=0.3,0.1

Chan Stop Cuts=-1
Use User Specified Reach Order=0
Composite Channel Slope=5